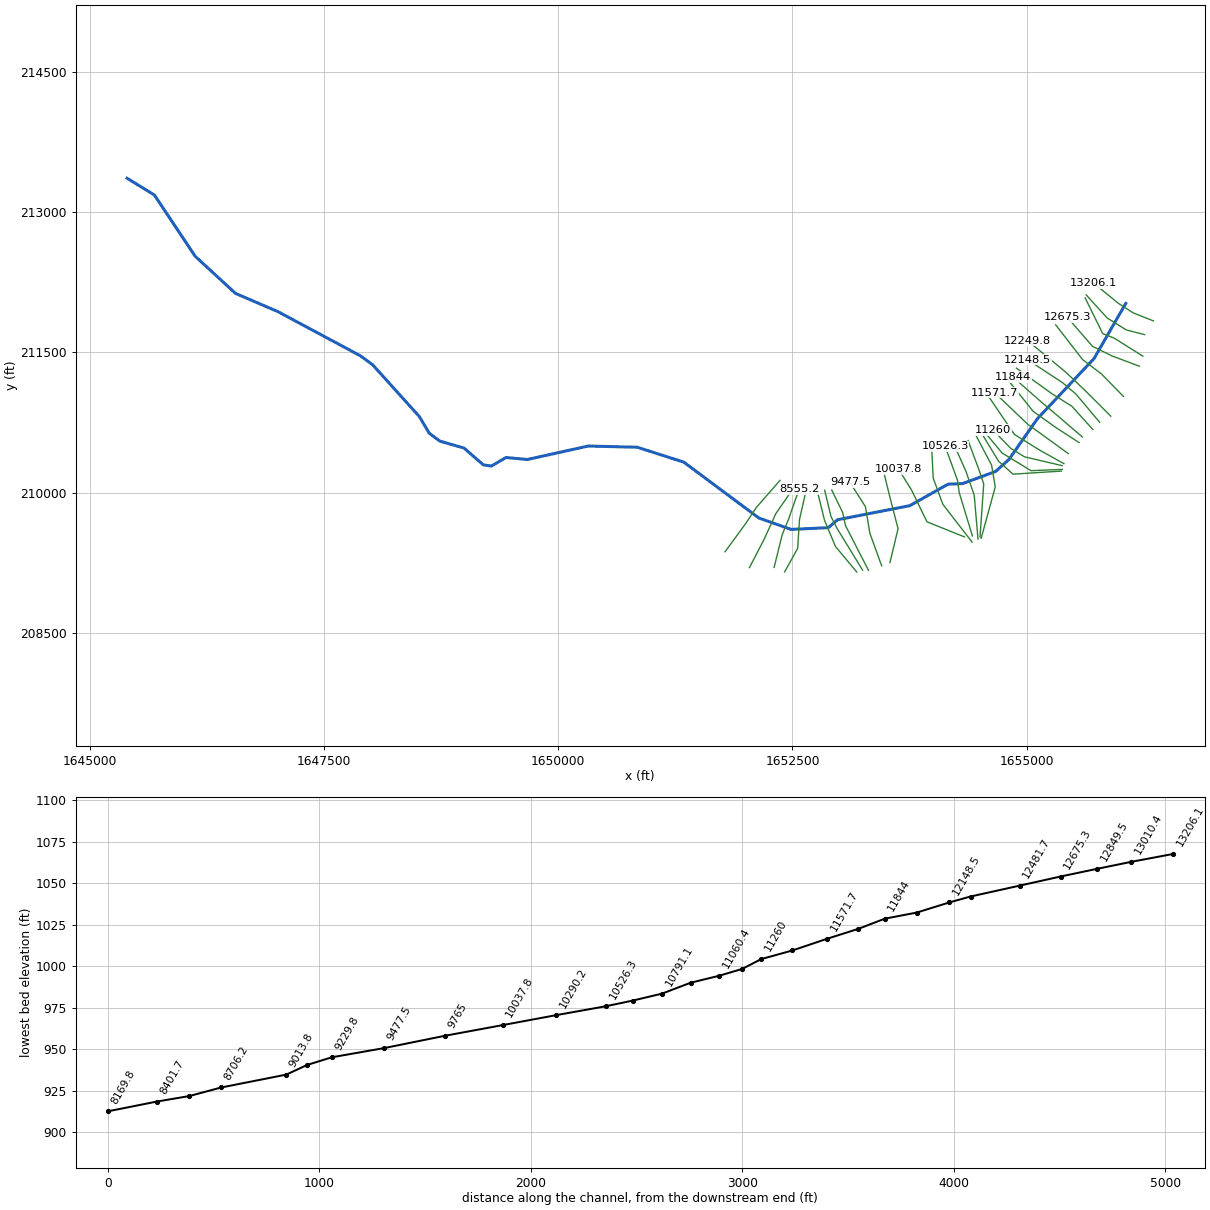
--- cnlyfrk.prj (project) ---

Proj Title=cnlyfrk
Current Plan=p01
Default Exp/Contr=0,0
English Units
Geom File=g01
Flow File=f01
Plan File=p01
BEGIN DESCRIPTION:
END DESCRIPTION:
DSS Export Rating Curves= 0
DSS Export Rating Curve Sorted= 0
DSS Export Volume Flow Curves= 0
DXF OffsetX= 0
DXF OffsetY= 0
DXF ScaleX= 0
DXF ScaleY= 0

--- cnlyfrk.p01 (plan) ---

Plan Title=Floodplain
Program Version=4.00
Geom File=g01
Flow File=f01
K Sum by GR=0
Std Step Tol=0.01
Critical Tol=0.01
Num of Std Step Trials=20
Max Error Tol=0.3
Flow Tol Ratio=0.001
Split Flow NTrial=30
Split Flow Tol=0.02
Split Flow Ratio=0.02
Log Output Level=0
Friction Slope Method=1
Unsteady Friction Slope Method=2
Unsteady Bridges Friction Slope Method=1
Global Log Level=0
CheckData=False
Run HTab=0
Run UNet=0
Run PostProcess=0
UNET Theta=0
UNET Theta Warmup=0
UNET ZTol=0
UNET ZSATol=0
UNET MxIter=0
UNET MaxInSteps=0
UNET DtIC=0
UNET DtMin=0
UNET MaxCRTS=0
UNET WFStab=0
UNET SFStab=0
UNET WFX=0
UNET SFX=0
UNET DSS MLevel=0
UNET DZMax Abort=0
UNET Convert EG Bridges=0
UNET Use Existing IB Tables=0
UNET Froude Limit=0
UNET Froude Power=0
Write IC File=0
Echo Input=False
Echo Output=False
Write Detailed=0

--- cnlyfrk.f01 (steady flow) ---

Flow Title=NFF Regression Equation
Program Version=4.00
Number of Profiles= 1
Profile Names=P100yr
River Rch & RM=cnlyfrk,Main            ,13206.1
     352
River Rch & RM=cnlyfrk,Main            ,13010.4
     363
River Rch & RM=cnlyfrk,Main            ,11260
     397
River Rch & RM=cnlyfrk,Main            ,10925.5
     543
River Rch & RM=cnlyfrk,Main            ,9765
     577
River Rch & RM=cnlyfrk,Main            ,6828.5
     631
River Rch & RM=cnlyfrk,Main            ,6489.7
     824
River Rch & RM=cnlyfrk,Main            ,4331.6
     880
River Rch & RM=cnlyfrk,Main            ,111.1
     973
Boundary for River Rch & Prof#=cnlyfrk,Main            , 1
Up Type= 0
Dn Type= 3
Dn Slope=0.022
DSS Import GetInterval= 0
DSS Import GetPeak= 0
DSS Import FillOption= 0

--- cnlyfrk.g01 (geometry) ---

Geom Title=USGS 10m DEM
Program Version=4.00

River Reach=cnlyfrk         ,Main
Reach XY= 30
      1656059.28      212022.881     1655721.081      211434.161
     1655115.902      210790.199     1654813.581      210356.822
     1654670.963      210227.057     1654315.638      210096.314
     1654161.807      210090.651      1653753.07      209860.677
     1652982.024      209710.295     1652882.914      209625.278
     1652485.429      209607.242     1652141.528       209728.56
     1651339.757      210326.193      1650842.53      210485.508
     1650318.292      210498.164     1649669.724      210354.363
     1649442.229      210375.666     1649284.727      210284.193
     1649199.067      210296.996     1648991.972      210477.006
     1648734.265       210551.22      1648622.39      210634.211
     1648514.303      210815.261     1648015.509      211368.619
     1647883.531      211464.592     1647005.958      211935.043
     1646552.074      212130.576      1646120.93      212527.911
      1645686.72      213181.904     1645394.958      213361.115

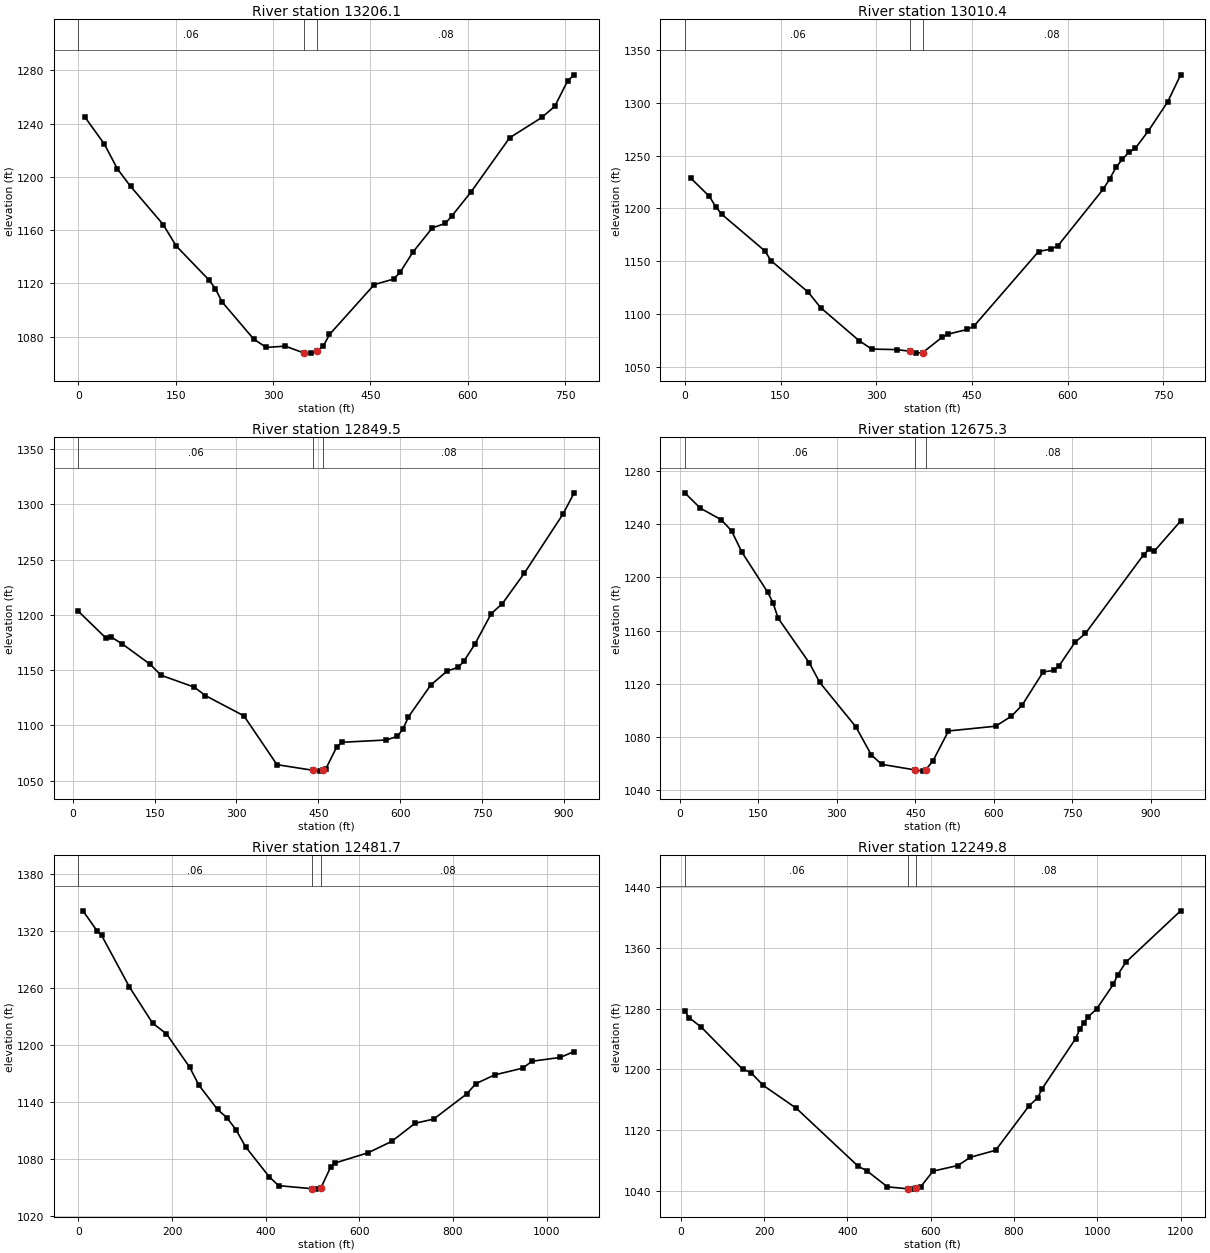
Type RM Length L Ch R = 1 ,13206.1 ,195.4,195.7,196
XS GIS Cut Line= 4
     1656355.332      211836.119     1656140.329      211921.222
     1655984.574      212021.065     1655714.998      212240.719
#Sta/Elev= 30
    10.1 1245.01    40.2  1224.6    60.3 1205.96    80.4 1192.99   130.7 1164.25
   150.8 1148.13   201.1 1122.68   211.1 1116.13   221.2 1106.26   270.2 1078.16
   289.7 1071.88   318.9 1072.85   347.8 1067.69   357.8  1067.6   367.8 1069.32
   377.3 1072.73     387  1081.6     456  1119.1   485.8 1123.25   495.7 1128.26
   515.6 1143.55   545.4 1161.67   565.3 1165.07   575.2 1170.45     605 1188.65
   664.6 1229.43   714.3 1244.74   734.2 1253.12     754 1272.24     764 1276.73
#Mann= 3 , 0 , 0
       0     .06       0   347.8    .045       0   367.8     .08       0
Bank Sta=347.8,367.8
XS Rating Curve= 0 ,0
Exp/Cntr=0.3,0.1

Type RM Length L Ch R = 1 ,13010.4 ,156.2,160.9,165.5
XS GIS Cut Line= 4
     1656261.023      211689.171     1656064.652      211739.906
     1655860.972      211867.205     1655636.326      212114.316
#Sta/Elev= 30
     9.7  1228.5    38.6 1211.32    48.3 1201.73    57.9 1194.44   125.6 1159.67
   135.2  1150.4   193.2 1120.76   212.8 1106.04   272.9 1074.84   292.9 1066.76
   332.9 1066.21   352.9 1064.66   362.9 1062.91   372.9 1063.47     403 1077.82
     413 1080.98     443 1085.38   453.1 1088.49   554.3 1159.12   574.6 1161.61
   584.7 1164.58   655.5 1218.07   665.6 1227.67   675.8 1238.96   685.9 1246.74
     696 1253.24   706.1 1257.03   726.4 1273.34   756.7 1300.91     777 1326.54
#Mann= 3 , 0 , 0
       0     .06       0   352.9    .045       0   372.9     .08       0
Bank Sta=352.9,372.9
XS Rating Curve= 0 ,0
Exp/Cntr=0.3,0.1

Type RM Length L Ch R = 1 ,12849.5 ,176.4,174.3,172.1
XS GIS Cut Line= 4
      1656242.38      211458.881     1655934.229      211652.983
       1655813.6      211700.138     1655626.077      212081.763
#Sta/Elev= 30
    10.1 1203.34    60.7 1179.11    70.8 1179.88      91 1173.65   141.6 1155.44
   161.9 1145.41   222.6 1134.71   242.8  1127.1   313.6 1108.72   374.2 1064.55
  440.04 1059.48   453.9 1058.71  458.04  1059.6   463.8 1060.87   483.7 1080.56
   493.7 1084.82   574.7 1086.89   594.9 1090.18   605.1 1096.85   615.2 1107.83
   655.7 1136.37   686.1 1149.32   706.3 1152.59   716.4 1157.91   736.7 1173.38
   767.1 1201.31   787.3 1210.23   827.8 1237.97   898.7 1291.48   918.9  1310.5
#Mann= 3 , 0 , 0
    10.1     .06       0  440.04    .045       0  458.04     .08       0
Bank Sta=440.04,458.04
XS Rating Curve= 0 ,0
Exp/Cntr=0.3,0.1

Type RM Length L Ch R = 1 ,12675.3 ,198.4,193.6,188.7
XS GIS Cut Line= 4
     1656204.228      211352.118     1655916.681      211459.948
     1655705.014      211563.785     1655433.664      211876.182
#Sta/Elev= 30
     9.9 1263.74    39.6 1252.17    79.3 1243.51    99.1 1235.18   118.9 1219.06
   168.4  1188.7   178.3 1180.88   188.2 1169.24   247.7 1135.57   267.5 1120.91
   336.6 1087.42     366 1066.33   385.7 1059.17  450.04  1054.9   464.3 1054.04
  470.03 1055.04   483.9 1061.87   513.4  1084.3   603.4 1087.89   633.7 1095.48
   653.9 1103.65   694.3 1128.83   714.4  1129.9   724.5 1133.31   754.8 1151.03
     775 1157.83     886 1217.07   896.1 1221.12   906.2 1219.68   956.7  1242.5
#Mann= 3 , 0 , 0
     9.9     .06       0  450.04    .045       0  470.03     .08       0
Bank Sta=450.04,470.03
XS Rating Curve= 0 ,0
Exp/Cntr=0.3,0.1

Type RM Length L Ch R = 1 ,12481.7 ,234.7,231.9,229.2
XS GIS Cut Line= 4
     1656034.699      211028.526     1655799.569      211269.646
     1655598.885      211422.406     1655311.338      211793.821
#Sta/Elev= 30
     9.9 1341.37    39.6 1320.55    49.5 1315.68     109 1261.33   158.5 1223.21
   188.2 1211.92   237.7 1176.83   257.5 1157.87   297.2 1132.34     317 1123.85
   336.8  1110.9     357 1093.12   407.4 1061.68   427.6 1052.19   498.3 1049.03
   508.3 1048.54   518.3 1050.18   538.6 1071.63   548.6  1076.1     619 1086.86
   668.9  1098.7   718.9  1117.8   758.9 1122.27   828.9 1148.56   848.8 1159.49
   888.8 1168.73   948.8 1175.83   968.8 1183.11  1028.7 1187.07  1058.7 1193.35
#Mann= 3 , 0 , 0
       0     .06       0   498.3    .045       0   518.3     .08       0
Bank Sta=498.3,518.3
XS Rating Curve= 0 ,0
Exp/Cntr=0.3,0.1

Type RM Length L Ch R = 1 ,12249.8 ,100,101.3,102.6
XS GIS Cut Line= 4
     1655899.819      210817.515     1655626.471      211090.863
     1655417.023      211289.661     1655012.327      211623.358
#Sta/Elev= 30
     9.9 1276.57    19.8 1268.17    49.6 1255.41   148.7 1200.07   168.5 1195.59
   198.2 1178.69   277.5 1148.59   426.4 1071.93   446.3 1066.42   496.1    1045
   545.9 1042.42   555.9 1041.99   565.9 1042.95   575.8 1044.89   605.6  1065.7
   665.4 1073.13   695.5 1084.05     756 1093.19   836.7  1152.2   856.9 1162.29
     867 1173.93   947.7 1240.18   957.8 1252.57   967.9 1261.25     978 1269.18
   998.1 1279.21  1038.5 1311.88  1048.6 1324.19  1068.7  1341.2  1199.9 1408.78
#Mann= 3 , 0 , 0
     9.9     .06       0   545.9    .045       0   565.9     .08       0
#XS Ineff= 2 , 0
       0     526                       0
Permanent Ineff=
       F       F
Bank Sta=545.9,565.9
XS Rating Curve= 0 ,0
Exp/Cntr=0.3,0.1

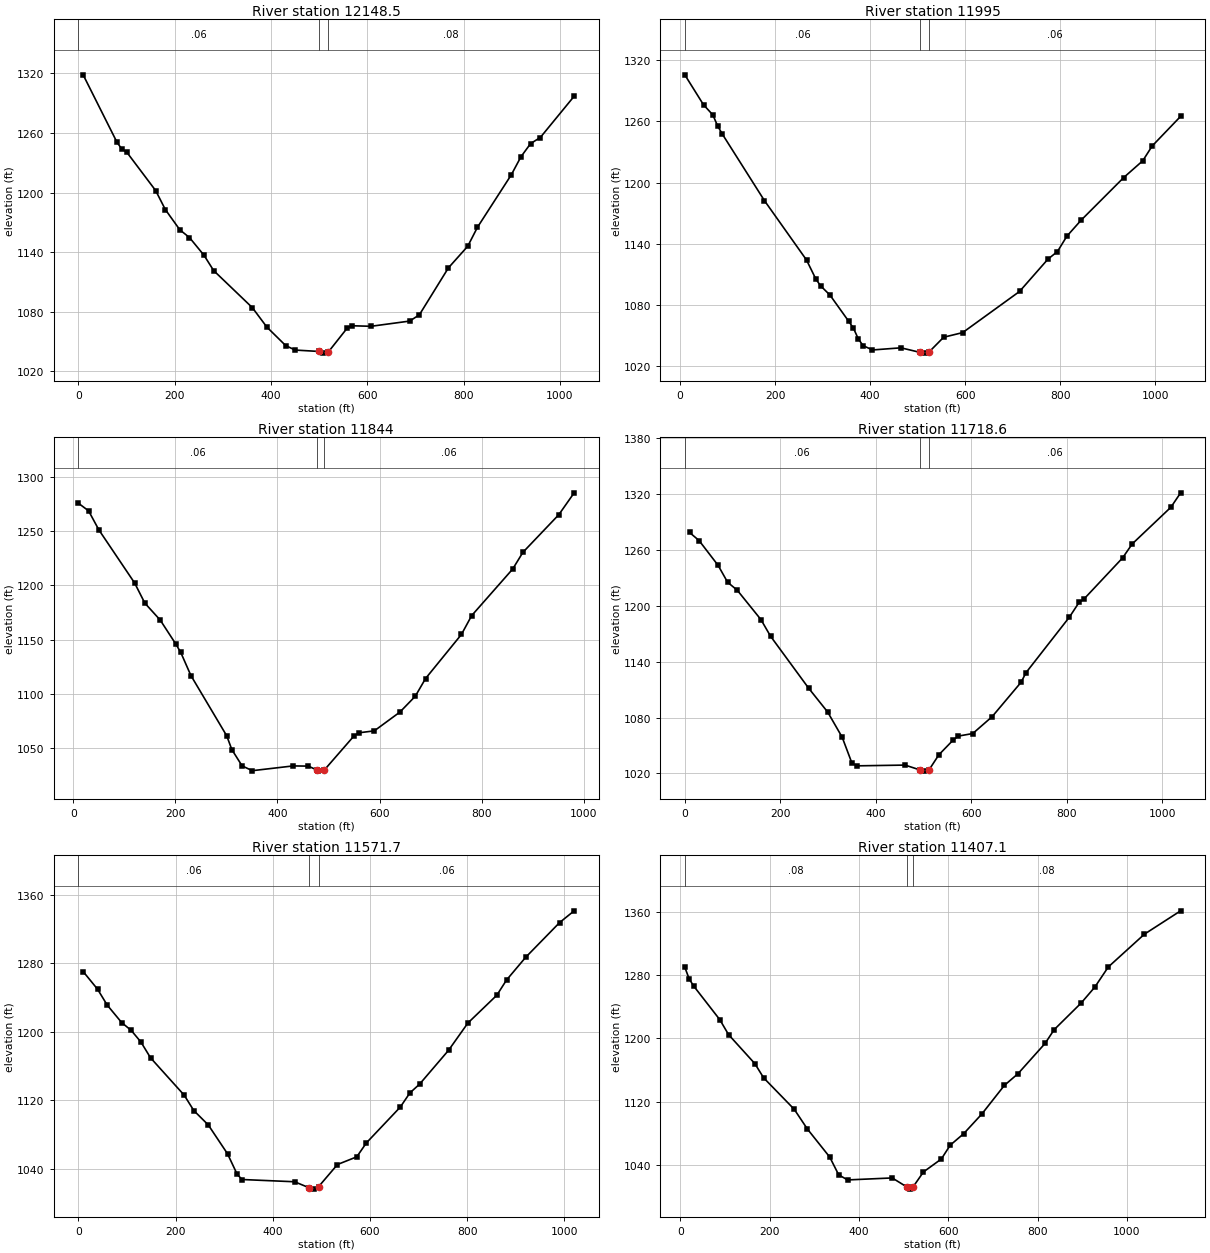
Type RM Length L Ch R = 1 ,12148.5 ,149.8,153.5,157.2
XS GIS Cut Line= 4
     1655780.999      210752.179     1655529.341      211051.994
     1655387.978      211173.163      1655010.49      211421.714
#Sta/Elev= 30
      10 1318.64    80.3 1250.68    90.3 1243.89   100.4 1240.86   160.6 1202.07
   180.7 1182.93   210.8 1162.55   230.8 1154.77     261 1136.92     281 1121.52
   361.3 1084.22   391.4 1064.67   430.6 1045.98   450.2 1041.48     499  1040.1
     509 1038.39     519 1039.46     558 1063.41   567.8 1065.95   607.8 1065.42
   688.1 1070.67   708.2 1076.99   768.5 1124.27   808.6 1146.01   828.7 1165.05
     899  1217.9   919.1 1236.11   939.2 1249.43   959.3 1255.52  1029.6  1297.1
#Mann= 3 , 0 , 0
       0     .06       0     499    .045       0     519     .08       0
Bank Sta=499,519
XS Rating Curve= 0 ,0
Exp/Cntr=0.3,0.1

Type RM Length L Ch R = 1 ,11995   ,154.5,150.9,147.4
XS GIS Cut Line= 4
     1655708.213      210675.082     1655483.567      210923.691
     1655272.399      211056.981     1654891.998      211331.049
#Sta/Elev= 30
     9.9 1305.84    49.3 1276.39      69 1266.42    78.8  1255.8    88.7 1247.74
   177.4  1182.3   266.1 1123.85   285.8 1105.07   295.7 1098.47   315.4  1089.4
     355 1063.54     365 1056.72     375  1046.4     385 1039.73     405 1035.41
   464.9 1037.52   504.9 1033.06   514.9  1032.3   524.9 1033.81   554.8 1047.93
   594.8 1052.47   714.5  1092.9   774.3 1124.66   794.3 1132.15   814.2 1147.26
   844.1 1162.95   933.9 1204.91   973.8 1221.32   993.8 1235.94  1053.6 1265.02
#Mann= 3 , 0 , 0
     9.9     .06       0   504.9    .045       0   524.9     .06       0
#XS Ineff= 2 , 0
       0     454                       0
Permanent Ineff=
       F       F
Bank Sta=504.9,524.9
XS Rating Curve= 0 ,0
Exp/Cntr=0.3,0.1

Type RM Length L Ch R = 1 ,11844   ,123.4,125.4,127.5
XS GIS Cut Line= 4
     1655596.139      210595.281     1655283.897      210862.474
     1655162.728      210965.001     1654853.593      211236.854
#Sta/Elev= 30
      10 1275.96    30.1 1268.88    50.1 1251.41   120.3 1202.27   140.3  1183.7
   170.4 1168.07   200.5 1146.27   210.5 1138.34   230.5 1116.89   300.7 1061.22
   310.7 1048.52   330.8 1033.48   350.8 1029.04   430.8 1033.44   460.6 1033.26
  476.97 1029.73   480.4 1028.63  492.07 1029.76   549.8 1061.01   559.8 1064.02
   589.8  1065.8     640 1083.15   670.1 1097.76   690.2 1114.11   760.5 1154.81
   780.5 1172.17   860.9 1215.18   880.9 1230.59   951.2 1265.32   981.3 1285.51
#Mann= 3 , 0 , 0
      10     .06       0  476.97    .045       0  492.07     .06       0
#XS Ineff= 2 , 0
       0     440                       0
Permanent Ineff=
       F       F
Bank Sta=476.97,492.07
XS Rating Curve= 0 ,0
Exp/Cntr=0.3,0.1

Type RM Length L Ch R = 1 ,11718.6 ,147,147,146.9
XS GIS Cut Line= 4
     1655559.946      210535.801     1655317.328      210693.054
     1655070.217      210869.775     1654791.656      211217.229
#Sta/Elev= 30
      10  1278.6    29.9 1269.94    69.8 1243.27    89.7 1225.15   109.7 1216.72
   159.5 1185.07   179.5 1167.32   259.2 1111.58   299.2  1085.9   329.6 1058.82
   349.9 1031.18     360 1028.15   461.3 1028.96   491.8 1023.88   501.8 1022.48
   511.8 1024.12   532.2 1040.11   562.5 1056.11   572.7 1060.08     603 1062.82
   643.5 1080.89   704.3 1117.91   714.4 1128.07   805.5 1187.84   825.7 1203.61
   835.8 1207.12   916.8 1251.34     937 1266.36    1018 1305.73  1038.3 1321.16
#Mann= 3 , 0 , 0
       0     .06       0   491.8    .045       0   511.8     .06       0
Bank Sta=491.8,511.8
XS Rating Curve= 0 ,0
Exp/Cntr=0.3,0.1

Type RM Length L Ch R = 1 ,11571.7 ,162.9,164.6,166.2
XS GIS Cut Line= 4
     1655446.231      210417.088     1655133.694      210644.089
     1655014.162      210729.626     1654662.146       211066.29
#Sta/Elev= 30
     9.9 1270.31    39.6 1249.69    59.4 1231.21    89.1 1210.86   108.9 1201.61
   128.8 1188.12   148.6  1169.7   217.9  1126.1   237.7 1108.14   267.4 1091.43
     307 1057.79   326.8 1033.97   336.8 1027.76   445.1 1025.13   474.3 1018.29
   484.3 1016.54   494.3 1019.34   533.3 1045.25     573  1054.2   592.9 1070.53
   662.5 1112.18   682.4  1128.8   702.3 1138.98   761.9 1178.45   801.7 1210.26
   861.3 1242.74   881.2 1260.42   920.9 1287.09   990.5 1327.46  1020.4 1341.13
#Mann= 3 , 0 , 0
       0     .06       0   474.3    .045       0   494.3     .06       0
Bank Sta=474.3,494.3
XS Rating Curve= 0 ,0
Exp/Cntr=0.3,0.1

Type RM Length L Ch R = 1 ,11407.1 ,147,147.1,147.2
XS GIS Cut Line= 4
     1655399.273       210309.87     1655150.776      210448.319
     1654870.328      210622.267     1654586.331      211041.163
#Sta/Elev= 30
     9.8 1289.71    19.6 1274.97    29.4 1266.16    88.3 1223.41   107.9 1204.55
   166.8 1167.91   186.4 1150.03     255 1110.27   284.5 1085.32   334.5 1049.94
   354.5 1027.56   374.5 1021.07   474.5 1023.59   507.6 1012.07   514.5 1009.46
  520.67 1011.83   544.5 1031.19   584.5  1047.5   604.5 1065.01   634.7 1079.54
   675.2 1104.29   725.8 1140.52   756.2 1155.21   816.9 1193.44   837.2  1210.8
   897.9 1244.58   928.3 1264.55   958.6 1290.05  1039.6  1331.5  1120.6 1360.93
#Mann= 3 , 0 , 0
     9.8     .08       0   507.6    .045       0  520.67     .08       0
Bank Sta=507.6,520.67
XS Rating Curve= 0 ,0
Exp/Cntr=0.3,0.1

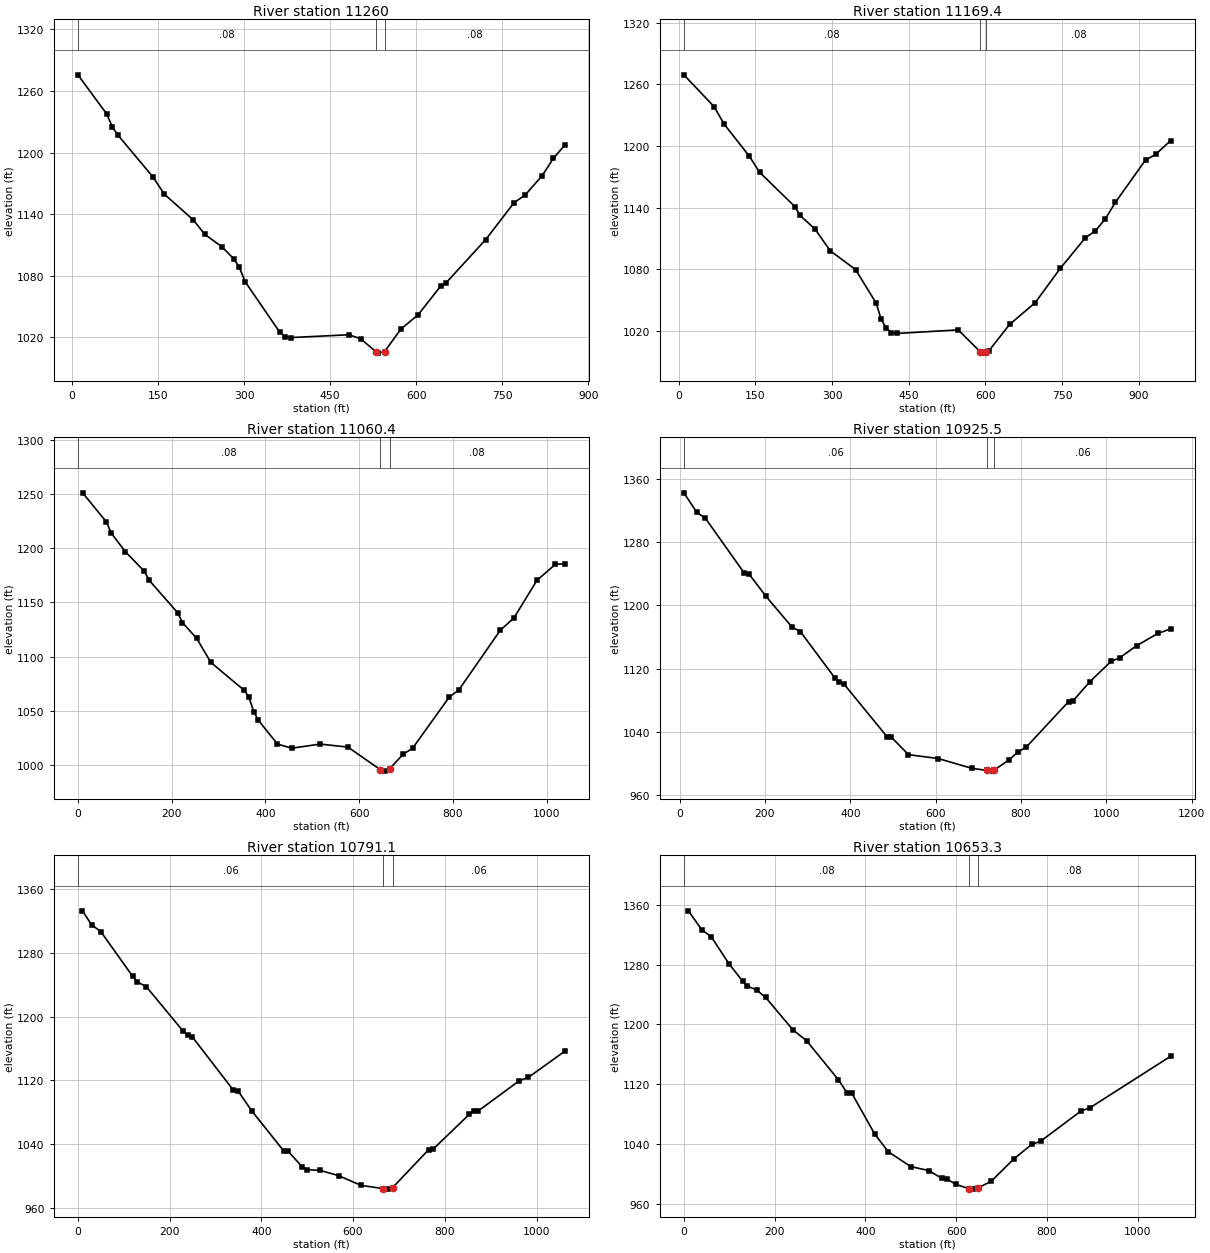
Type RM Length L Ch R = 1 ,11260   ,90.5,90.6,90.7
XS GIS Cut Line= 4
     1655379.337      210288.783     1654977.973      210383.093
     1654832.122      210473.016     1654640.213      210670.408
#Sta/Elev= 30
    10.1 1275.78    60.3 1237.65    70.4 1224.73    80.4 1216.64   140.8 1176.29
   160.9 1159.33   211.2 1134.34   231.3 1120.17   261.5 1107.94   281.6 1096.39
   291.6 1088.07   301.7 1074.03     362 1024.79   372.1 1020.01   382.1 1019.47
   482.8  1022.2     503 1018.28  529.95 1005.68   533.2 1004.28  544.87 1005.76
   573.6 1027.89   603.3 1041.59   642.6 1069.57   652.5 1073.08   721.3 1115.08
   770.5 1150.88   790.1 1158.57   819.6 1177.33   839.3 1194.29   858.9 1207.08
#Mann= 3 , 0 , 0
    10.1     .08       0  529.95    .045       0  544.87     .08       0
Bank Sta=529.95,544.87
XS Rating Curve= 0 ,0
Exp/Cntr=0.3,0.1

Type RM Length L Ch R = 1 ,11169.4 ,113.7,109.1,104.5
XS GIS Cut Line= 4
     1655383.225      210248.254     1655047.753      210234.775
     1654739.238      210423.478     1654570.005      210627.157
#Sta/Elev= 30
     9.9  1269.3    69.1 1238.31    88.9 1221.21   138.2 1189.94     158 1174.47
   227.1    1141     237 1132.53   266.6 1119.08   296.2 1098.03   345.8 1079.67
     386 1047.15     396 1031.16   406.1 1022.47   416.1 1018.27   426.2 1017.46
   546.7 1020.96  589.85  999.58   596.9  998.33   601.8   999.5     607 1000.74
   647.2 1026.26   697.4 1047.51   746.4 1080.87   795.5 1110.66   815.1 1117.34
   834.7 1129.22   854.3  1145.2   913.2 1186.39   932.8 1191.76   962.2 1205.25
#Mann= 3 , 0 , 0
     9.9     .08       0  589.85    .045       0   601.8     .08       0
Bank Sta=589.85,601.8
XS Rating Curve= 0 ,0
Exp/Cntr=0.3,0.1

Type RM Length L Ch R = 1 ,11060.4 ,153.1,134.9,116.7
XS GIS Cut Line= 4
      1655370.89      210230.222     1654855.146      210197.599
     1654701.355      210335.856     1654538.243      210604.602
#Sta/Elev= 30
    10.1 1251.25    60.8 1224.38    70.9  1214.2   101.3 1196.82   141.9 1178.71
     152 1170.45   212.8 1140.47   222.9 1131.47   253.3 1116.78   283.7 1094.54
   354.6 1068.86   364.8 1062.48   374.9 1049.15     385 1041.09   425.6 1019.18
     456 1015.37   516.8 1019.19   575.9 1016.39   644.6  995.63   654.6   994.2
   664.6  996.31     694 1009.96   713.7 1015.34   792.3 1062.82     812    1069
   900.4 1124.13   929.9 1135.78     979 1170.46  1018.3 1185.26  1037.9 1185.67
#Mann= 3 , 0 , 0
       0     .08       0   644.6    .045       0   664.6     .08       0
Bank Sta=644.6,664.6
XS Rating Curve= 0 ,0
Exp/Cntr=0.3,0.1

Type RM Length L Ch R = 1 ,10925.5 ,130.5,134.4,138.3
XS GIS Cut Line= 4
      1654516.09      209514.409     1654665.854      210061.049
     1654626.915      210293.183      1654465.17      210601.698
#Sta/Elev= 30
    10.1 1342.71    40.5 1317.89    60.7 1310.42   151.8  1240.9   161.9 1240.42
   202.4 1211.65   263.1 1172.83   283.4 1166.62   364.4 1107.74   374.5 1102.55
   384.6 1100.84   485.8 1033.85   495.9 1033.23   536.4 1010.86     606 1005.98
   684.5  993.61  720.01  990.91   733.5     990  737.77  991.49   772.7 1004.51
   792.4 1014.14   812.1  1020.3   911.6 1078.18   921.6 1078.84   961.4 1103.35
  1011.2 1129.23  1031.1 1133.55  1070.9    1149  1120.6 1164.46  1150.5 1170.28
#Mann= 3 , 0 , 0
    10.1     .06       0  720.01    .045       0  737.77     .06       0
Bank Sta=720.01,737.77
XS Rating Curve= 0 ,0
Exp/Cntr=0.3,0.1

Type RM Length L Ch R = 1 ,10791.1 ,137.9,137.8,137.8
XS GIS Cut Line= 4
     1654503.135      209525.533     1654542.614      210092.488
     1654489.976      210250.402     1654375.927      210556.359
#Sta/Elev= 30
      10  1333.1    29.9  1315.5    49.9 1307.07   119.6 1250.71   129.6 1243.88
   149.6 1237.53   229.3 1182.02   239.3 1176.99   249.3 1174.91     339 1107.79
     349 1106.93   378.9 1081.95   448.7 1031.55   458.6 1030.97   488.6 1011.72
   498.5 1008.07   528.4 1006.99   568.3 1000.44   617.3  988.21     666  984.05
     676  983.46     686  985.23   764.5 1032.86   774.4 1033.56   853.5 1077.46
   863.4 1081.36   873.3 1081.88   962.4 1119.62   982.1 1123.79  1061.3 1156.55
#Mann= 3 , 0 , 0
       0     .06       0     666    .045       0     686     .06       0
Bank Sta=666,686
XS Rating Curve= 0 ,0
Exp/Cntr=0.3,0.1

Type RM Length L Ch R = 1 ,10653.3 ,131.6,127,122.4
XS GIS Cut Line= 4
     1654481.644      209503.926     1654441.207      209972.688
     1654354.344      210224.292     1654218.059      210531.308
#Sta/Elev= 30
      10 1351.88      40 1326.19    60.1 1317.32   100.1 1280.45   130.1  1257.3
   140.1 1251.17   160.2 1245.85   180.2 1235.98   240.3 1192.56   270.3  1178.1
   340.4 1125.83   360.4  1107.6   370.4 1107.38   420.4 1053.17   450.5 1029.31
   500.1 1009.47   539.5 1004.15   569.1  993.57   578.9  993.33   598.7  985.78
   628.1  979.96   638.1  979.29   648.1  980.85   677.5  989.89   726.8 1019.44
   766.3 1039.11   786.1 1043.39     875 1083.81   894.8 1088.15  1072.6 1157.15
#Mann= 3 , 0 , 0
       0     .08       0   628.1    .045       0   648.1     .08       0
Bank Sta=628.1,648.1
XS Rating Curve= 0 ,0
Exp/Cntr=0.3,0.1

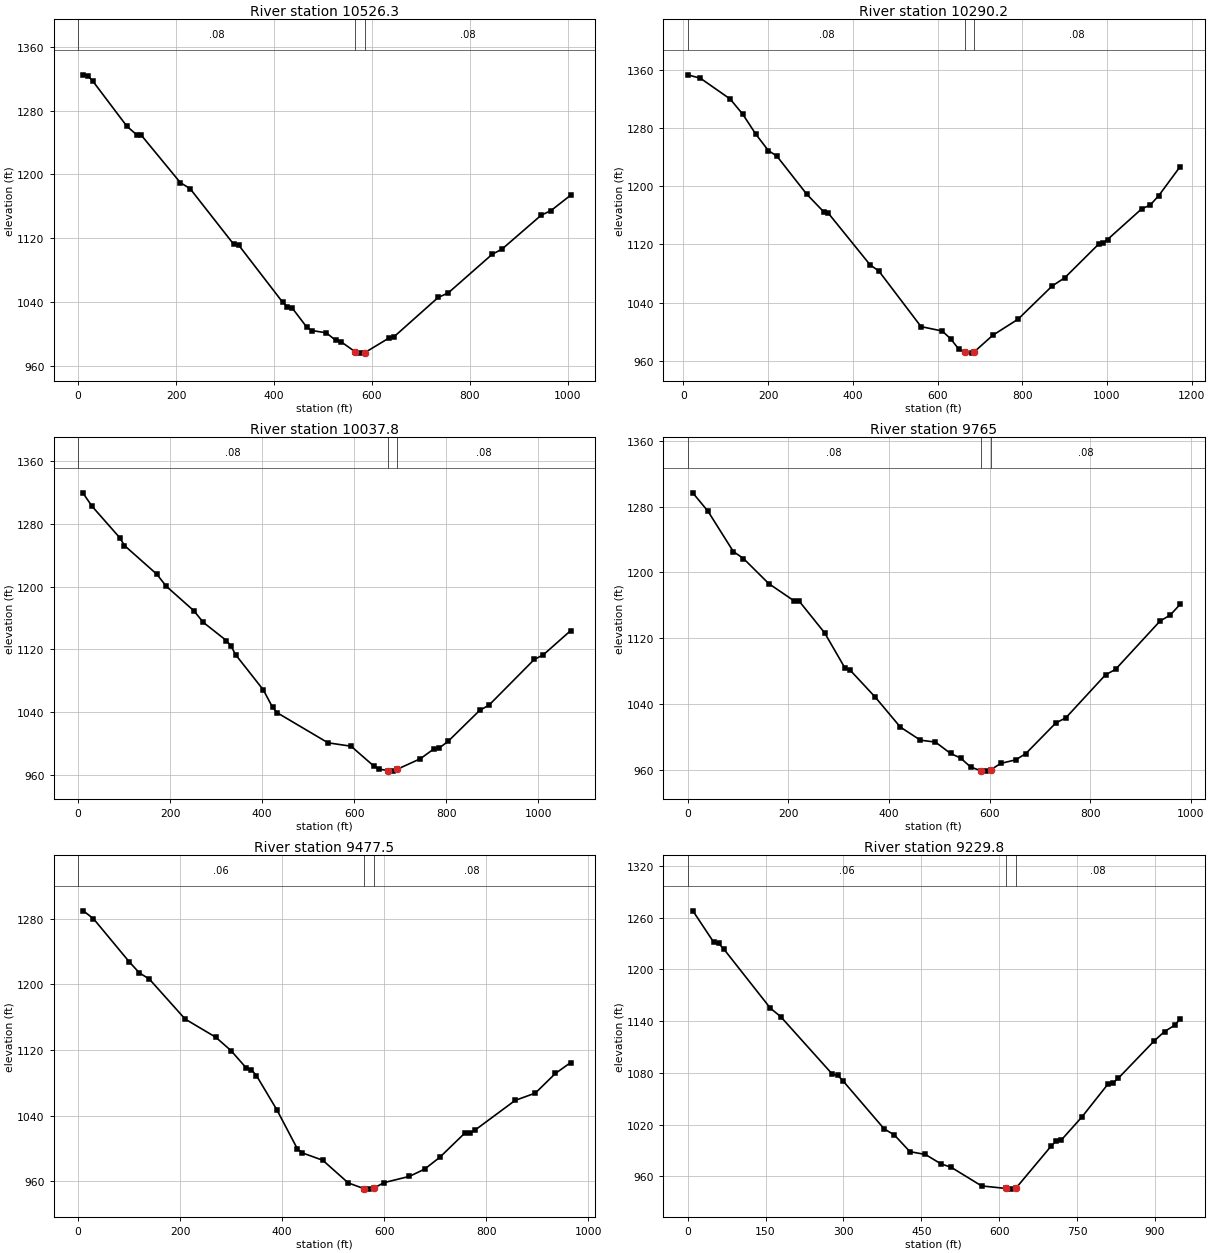
Type RM Length L Ch R = 1 ,10526.3 ,230.7,236.2,241.6
XS GIS Cut Line= 4
     1654421.735      209537.385     1654280.371      210003.419
     1654263.284      210130.801     1654129.687      210497.414
#Sta/Elev= 30
     9.9 1324.74    19.9 1323.45    29.8 1316.97    99.4 1260.34   119.3 1249.71
   129.2 1248.87   208.7  1189.6   228.6 1182.11     318 1112.08     328 1111.18
   417.4 1039.88   427.4 1034.26   437.3 1032.32   467.1 1008.32   477.1 1004.22
   506.8 1001.33   526.5  991.72   536.4  990.38     566  977.47     576  975.87
     586  976.65   635.5  995.04   645.5  996.55   735.6  1045.8   755.6 1051.17
   845.6 1099.72   865.7 1106.21   945.7 1148.73   965.7 1154.48  1005.7 1173.71
#Mann= 3 , 0 , 0
       0     .08       0     566    .045       0     586     .08       0
Bank Sta=566,586
XS Rating Curve= 0 ,0
Exp/Cntr=0.3,0.1

Type RM Length L Ch R = 1 ,10290.2 ,249.8,252.4,255
XS GIS Cut Line= 4
     1654418.373      209470.969     1654105.976      209875.665
     1654003.027      210156.112     1653985.277      210518.209
#Sta/Elev= 30
      10 1353.41    40.1 1348.72   110.3 1320.13   140.3 1299.04   170.4 1272.14
   200.5  1249.2   220.5 1241.65   290.7 1189.47   330.8 1165.13   340.8 1163.94
   441.1 1091.68   461.1 1083.66     561 1006.95   610.8 1000.93   630.7  990.36
   650.7   975.5  665.44   971.4   680.5  970.48  685.13  971.46   730.3  995.03
   790.1 1017.18   870.4 1062.76   900.6  1074.3   981.2 1120.97   991.3 1122.04
  1001.3 1126.79  1081.9 1168.98    1102 1174.19  1122.2 1187.12  1172.5 1226.92
#Mann= 3 , 0 , 0
      10     .08       0  665.44    .045       0  685.13     .08       0
Bank Sta=665.44,685.13
XS Rating Curve= 0 ,0
Exp/Cntr=0.3,0.1

Type RM Length L Ch R = 1 ,10037.8 ,277.7,272.8,267.8
XS GIS Cut Line= 4
      1654337.87       209526.39     1653936.502      209688.136
     1653770.264      210031.096     1653633.978      210248.254
#Sta/Elev= 30
    10.1 1319.86    30.2 1302.67    90.6  1262.4   100.6 1252.59   171.1 1215.85
   191.2 1200.73   251.6  1169.2   271.7 1154.59     322 1131.26   332.1 1124.36
   342.2 1113.22   402.5 1068.18   422.7 1045.81   432.7    1039   543.1 1000.65
   593.2   996.3   643.4  970.58   653.4   967.1   673.5  965.27   683.5  964.49
   693.5  966.87   743.7  980.28   773.7  993.08   783.8  993.59   803.8 1002.36
     873 1042.21   892.7 1048.57   991.4 1107.09  1011.1 1113.01  1070.2 1143.73
#Mann= 3 , 0 , 0
       0     .08       0   673.5    .045       0   693.5     .08       0
Bank Sta=673.5,693.5
XS Rating Curve= 0 ,0
Exp/Cntr=0.3,0.1

Type RM Length L Ch R = 1 ,9765    ,289.7,287.5,285.3
XS GIS Cut Line= 4
     1653541.125      209252.322     1653627.988      209614.751
     1653538.129      209962.204     1653479.721      210201.827
#Sta/Elev= 30
    10.1 1296.77    40.3  1274.4    90.7 1225.32   110.8 1216.83   161.2 1186.23
   211.5 1165.27   221.6 1164.89     272 1126.44   312.3 1083.73   322.3  1081.3
   372.7 1048.09   422.5 1011.69   462.4  995.73   492.3  993.42   522.2  979.61
   542.2  974.01   562.1  963.13     582  958.61     592  958.07     602  959.59
   621.9  967.47   651.8  971.81   671.8  979.41   731.6 1016.76   751.3 1022.92
   830.2 1075.33     850 1081.85   938.8 1140.93   958.5 1147.83   978.2 1160.96
#Mann= 3 , 0 , 0
       0     .08       0     582    .045       0     602     .08       0
Bank Sta=582,602
XS Rating Curve= 0 ,0
Exp/Cntr=0.3,0.1

Type RM Length L Ch R = 1 ,9477.5  ,246.6,247.7,248.8
XS GIS Cut Line= 4
     1653452.764      209217.876     1653326.962      209565.329
     1653279.037      209851.379     1653114.296      210108.973
#Sta/Elev= 30
      10 1289.34      30 1279.77    99.9 1227.45   119.8 1213.94   139.8  1206.1
   209.7 1157.64   269.7 1135.54   299.6 1119.28   329.6 1098.05   339.6 1096.02
   349.6 1088.73   389.5 1047.23   429.5 1000.03   439.5  994.73   479.5  985.79
   529.5  958.21   559.6   951.4   569.6  950.64   579.6  951.83   599.6  958.51
   649.6   966.2   679.3  975.01   708.9  989.31   758.2 1018.92   768.1  1018.7
   777.9  1022.4   856.8 1058.64   896.3 1067.51   935.7 1091.43   965.3 1104.54
#Mann= 3 , 0 , 0
       0     .06       0   559.6    .045       0   579.6     .08       0
Bank Sta=559.6,579.6
XS Rating Curve= 0 ,0
Exp/Cntr=0.3,0.1

Type RM Length L Ch R = 1 ,9229.8  ,110.8,117.4,124.1
XS GIS Cut Line= 4
     1653312.202      209169.131     1653066.558      209647.259
      1653036.95       209786.53     1652919.611      210027.787
#Sta/Elev= 30
      10 1267.85    49.8 1231.72    59.7 1229.99    69.7 1223.43   159.3 1154.91
   179.2  1145.1   278.7 1078.31   288.7 1077.21   298.6 1071.01   378.3 1015.03
   398.2 1007.79     428  988.55   457.9  985.25   487.8   974.4   507.7  970.35
     566  948.82     613  945.86     623  945.09     633  946.79   699.8  994.86
   709.7 1001.03   719.7 1002.13   759.4 1028.89   809.1 1066.71     819 1068.25
     829  1073.5   898.5 1117.03   918.4 1127.89   938.3 1135.29   948.2  1142.5
#Mann= 3 , 0 , 0
       0     .06       0     613    .045       0     633     .08       0
Bank Sta=613,633
XS Rating Curve= 0 ,0
Exp/Cntr=0.3,0.1

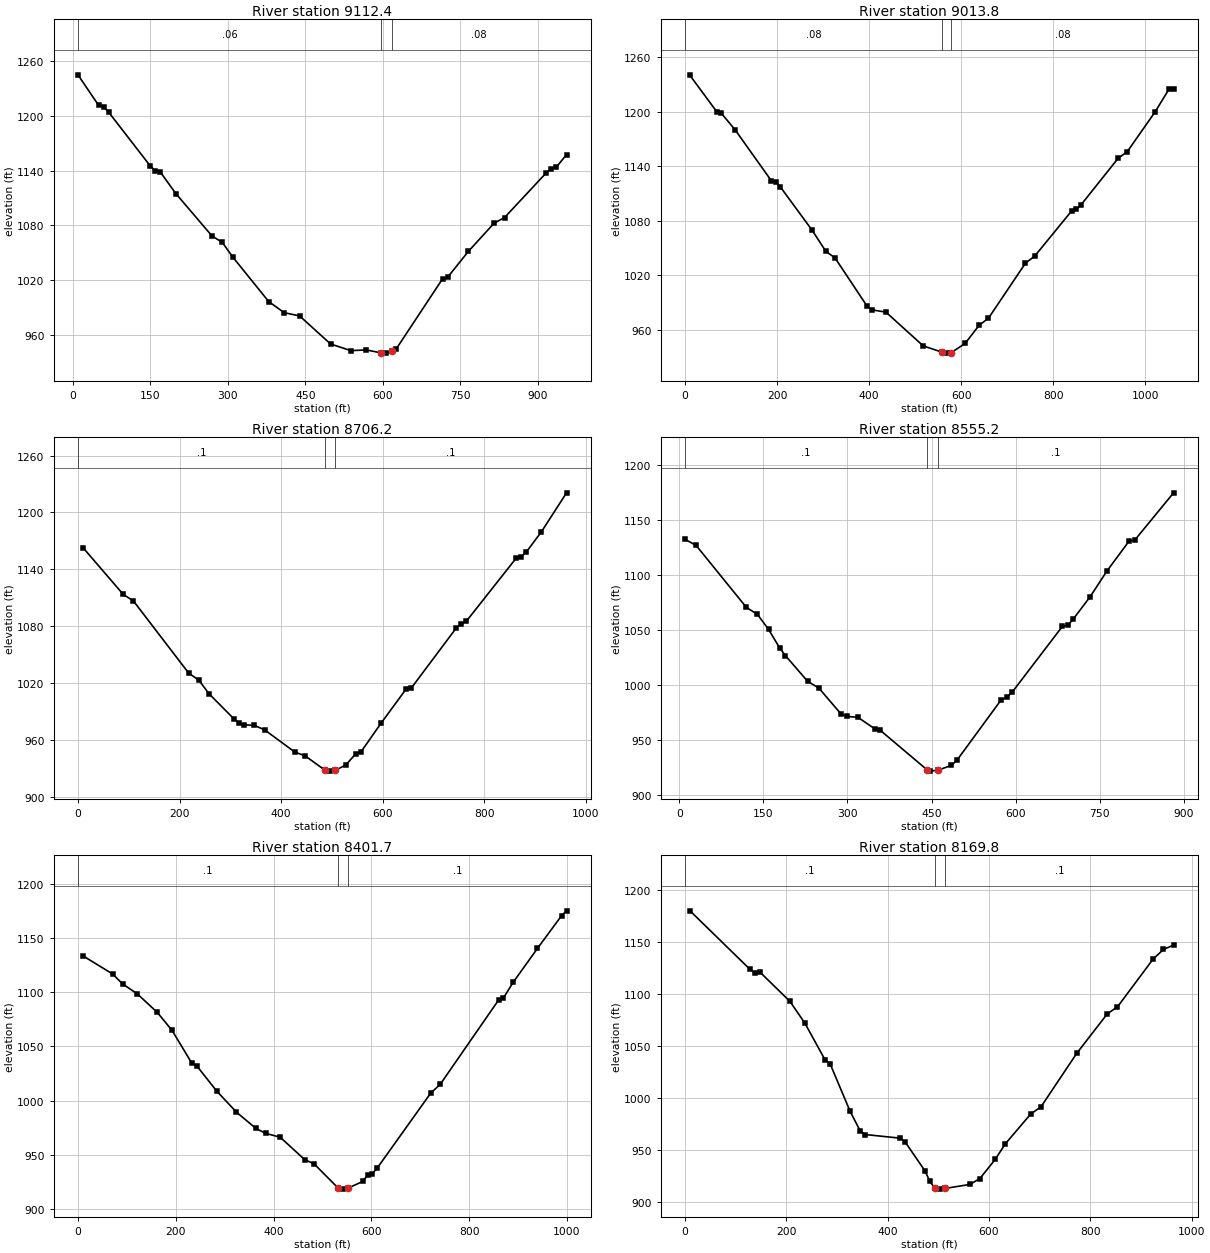
Type RM Length L Ch R = 1 ,9112.4  ,100.7,98.6,96.4
XS GIS Cut Line= 4
     1653249.143       209171.29     1652978.844      209614.022
     1652911.657      209744.317     1652844.082      210026.267
#Sta/Elev= 30
      10 1244.59    49.9 1211.28    59.9 1209.54    69.8 1203.46   149.6 1145.21
   159.6  1139.7   169.6 1138.13   199.5 1114.72   269.3  1068.5   289.3 1061.44
   309.2 1045.67   379.1  996.77     409  984.67   438.9   981.1   498.8  950.42
   538.3  943.15   567.6  943.99   596.7  940.72   606.7  940.46   616.7  942.41
   626.2  945.43   715.3 1021.56   725.3 1023.42   765.3 1051.61   815.3 1082.57
   835.3 1088.59   915.3 1137.03   925.3 1141.74   935.3 1143.54   955.3 1157.42
#Mann= 3 , 0 , 0
      10     .06       0   596.7    .045       0   616.7     .08       0
#XS Ineff= 2 , 0
       0     567                       0
Permanent Ineff=
       F       F
Bank Sta=596.7,616.7
XS Rating Curve= 0 ,0
Exp/Cntr=0.3,0.1

Type RM Length L Ch R = 1 ,9013.8  ,319.3,307.7,296
XS GIS Cut Line= 4
     1653186.535      209151.471     1652959.337      209424.819
     1652842.188      209705.266     1652746.339      210095.763
#Sta/Elev= 30
     9.9 1240.38    69.1 1199.79      79 1198.13   108.6 1180.16   187.6 1124.03
   197.5 1122.67   207.3 1117.18   276.5 1069.42   306.1 1046.39   325.8 1039.37
     396  985.94   406.1  982.17   436.5  979.69   517.5  942.63   558.2   935.7
   568.2  934.63   578.2  935.07   608.7  945.33   639.1   965.2   659.4  973.01
   739.8 1033.52   759.9 1041.24   840.3 1091.01   850.4  1092.6   860.4 1097.51
   940.8 1148.52   960.9 1155.93  1021.3 1199.61  1051.4 1224.48  1061.5 1225.12
#Mann= 3 , 0 , 0
       0     .08       0   558.2    .045       0   578.2     .08       0
Bank Sta=558.2,578.2
XS Rating Curve= 0 ,0
Exp/Cntr=0.3,0.1

Type RM Length L Ch R = 1 ,8706.2  ,159.2,150.9,142.7
XS GIS Cut Line= 4
     1652416.395       209151.98     1652555.676      209403.584
     1652575.145      209712.098     1652656.018      210068.537
#Sta/Elev= 30
     9.9 1162.86    89.2 1113.43   109.1 1106.64   218.2 1030.27     238 1022.99
   257.8 1008.74   307.5  981.86   317.5  977.65   327.5  975.84   347.4  975.13
   367.4  970.54   427.2  946.94   447.1   943.1     487  927.67     497  926.88
     507  927.91   526.9  933.07   546.9  945.04   556.8  946.79   596.7  977.34
   646.1 1013.45     656 1014.27   744.9 1077.93   754.8 1082.55   764.6 1084.96
   863.4 1152.04   873.3 1153.47   883.2 1158.38   912.8 1179.68   962.2 1220.73
#Mann= 3 , 0 , 0
       0      .1       0     487    .045       0     507      .1       0
Bank Sta=487,507
XS Rating Curve= 0 ,0
Exp/Cntr=0.3,0.1

Type RM Length L Ch R = 1 ,8555.2  ,154.5,153.6,152.7
XS GIS Cut Line= 4
      1652304.39      209200.288     1652389.829      209548.259
     1652456.627      209711.371     1652571.582      210039.148
#Sta/Elev= 30
      10 1132.65    29.9 1127.07   119.4 1070.79   139.3 1064.27   159.2 1050.64
   179.2  1033.6   189.1 1026.87   228.9 1003.41   248.8  997.35   288.6  973.65
   298.6  971.51   318.5  970.69   348.4  960.32   358.3  958.93   441.8  922.99
   446.4  921.71   461.6  922.52   485.6  927.05   495.4  931.66   574.3  986.62
   584.2  988.88   594.1  993.69   683.4 1053.35   693.4 1054.52   703.3 1060.32
   733.1 1080.45   762.8 1103.66   802.5    1131   812.4 1131.75   881.9 1174.94
#Mann= 3 , 0 , 0
      10      .1       0   441.8    .045       0   461.6      .1       0
Bank Sta=441.8,461.6
XS Rating Curve= 0 ,0
Exp/Cntr=0.3,0.1

Type RM Length L Ch R = 1 ,8401.7  ,235.9,231.9,227.8
XS GIS Cut Line= 4
     1652040.487      209198.407     1652194.744       209494.94
     1652322.044      209774.999     1652525.723      210068.537
#Sta/Elev= 30
    10.1 1133.49    70.9 1116.72    91.2  1107.6   121.5 1098.34   162.1 1081.37
   192.5 1064.68     233 1034.39   243.1    1032   283.6 1008.85   324.1  989.36
     364  974.31   383.9  969.82   413.6  966.23   463.3   945.7   483.1  941.61
   532.7  919.09   542.7  918.39   552.7  919.39   582.3  925.44   592.3  931.23
   602.2  932.77   612.1  937.86   721.3 1006.83   741.1 1015.16   860.2 1092.72
   870.2 1094.64     890 1109.07   939.6 1140.24   989.2 1170.62   999.2 1174.97
#Mann= 3 , 0 , 0
       0      .1       0   532.7    .045       0   552.7      .1       0
Bank Sta=532.7,552.7
XS Rating Curve= 0 ,0
Exp/Cntr=0.3,0.1

Type RM Length L Ch R = 1 ,8169.8  ,233.5,230.9,228.4
XS GIS Cut Line= 4
     1651780.361      209367.995     1651995.902      209662.761
     1652115.905      209843.349     1652367.563      210131.125
#Sta/Elev= 30
     9.9 1180.42   128.3 1124.07   138.2 1120.81     148 1121.42   207.3 1093.14
   236.9 1072.05   276.3 1037.08   286.2 1033.39   325.7  987.65   345.4  968.87
   355.3  965.08   424.3  961.59   434.2  958.16   473.6   930.1   483.4  919.91
   493.1  913.37   503.1   912.5   513.1  913.14   562.3  917.03     582  922.68
   612.2  941.05   632.3  956.14   682.6  984.93   702.7  991.77   773.1 1043.17
   833.5 1081.26   853.6 1087.96     924 1134.01   944.2  1143.2   964.3 1147.46
#Mann= 3 , 0 , 0
       0      .1       0   493.1    .045       0   513.1      .1       0
Bank Sta=493.1,513.1
XS Rating Curve= 0 ,0
Exp/Cntr=0.3,0.1