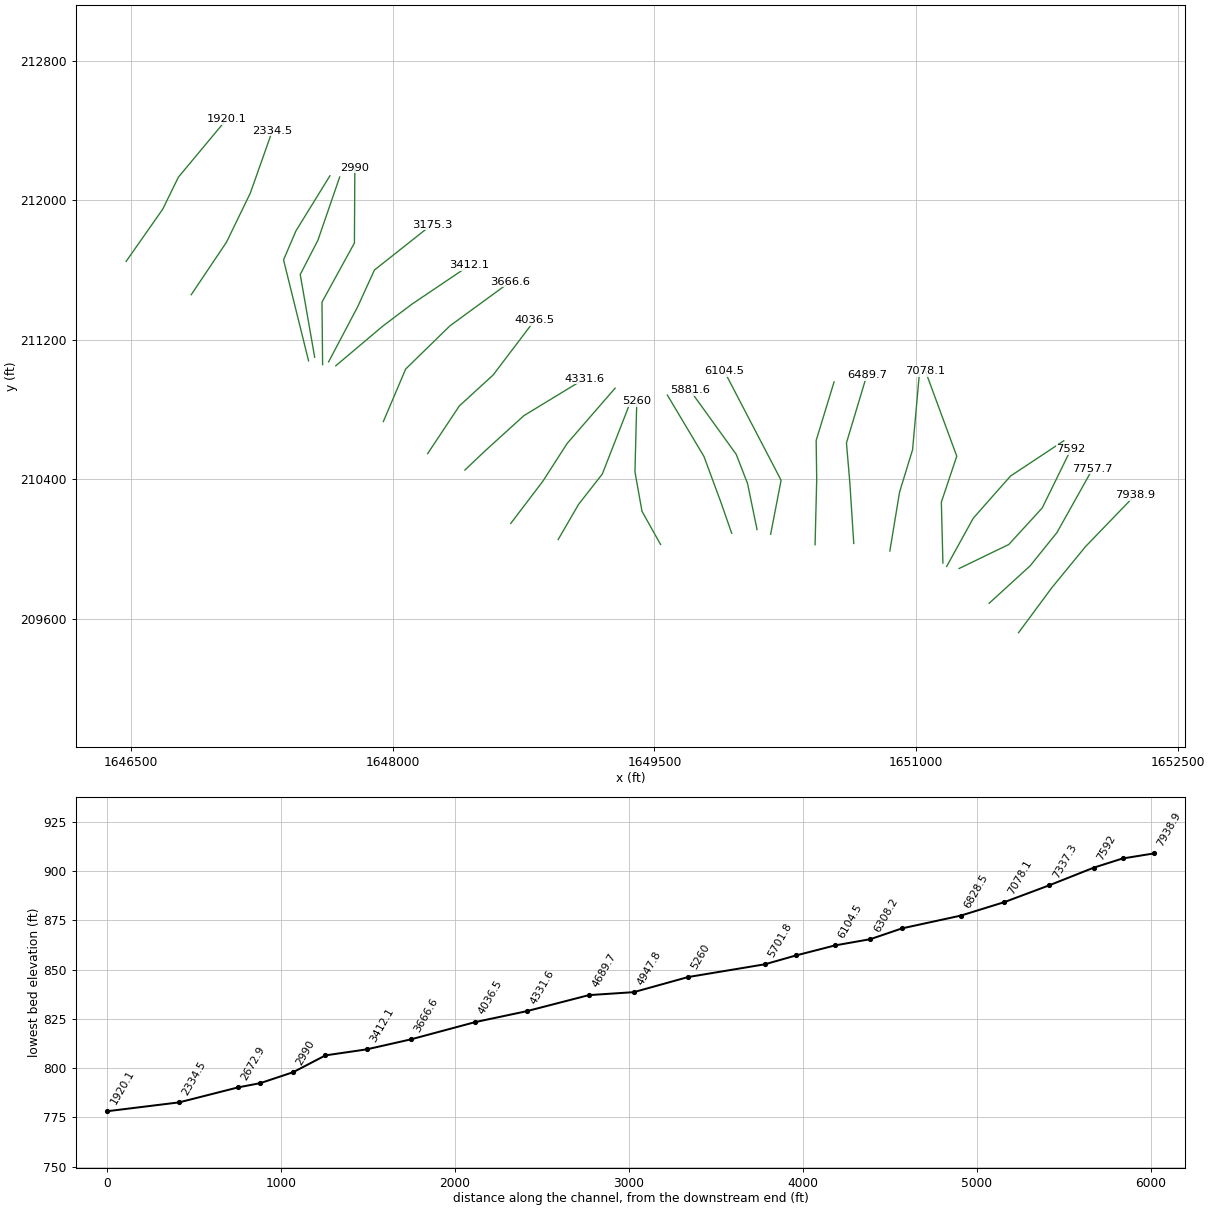
HEC-RAS study cnlyfrk.prj: cnlyfrk

--- cnlyfrk.g01 (geometry) --- (continued)

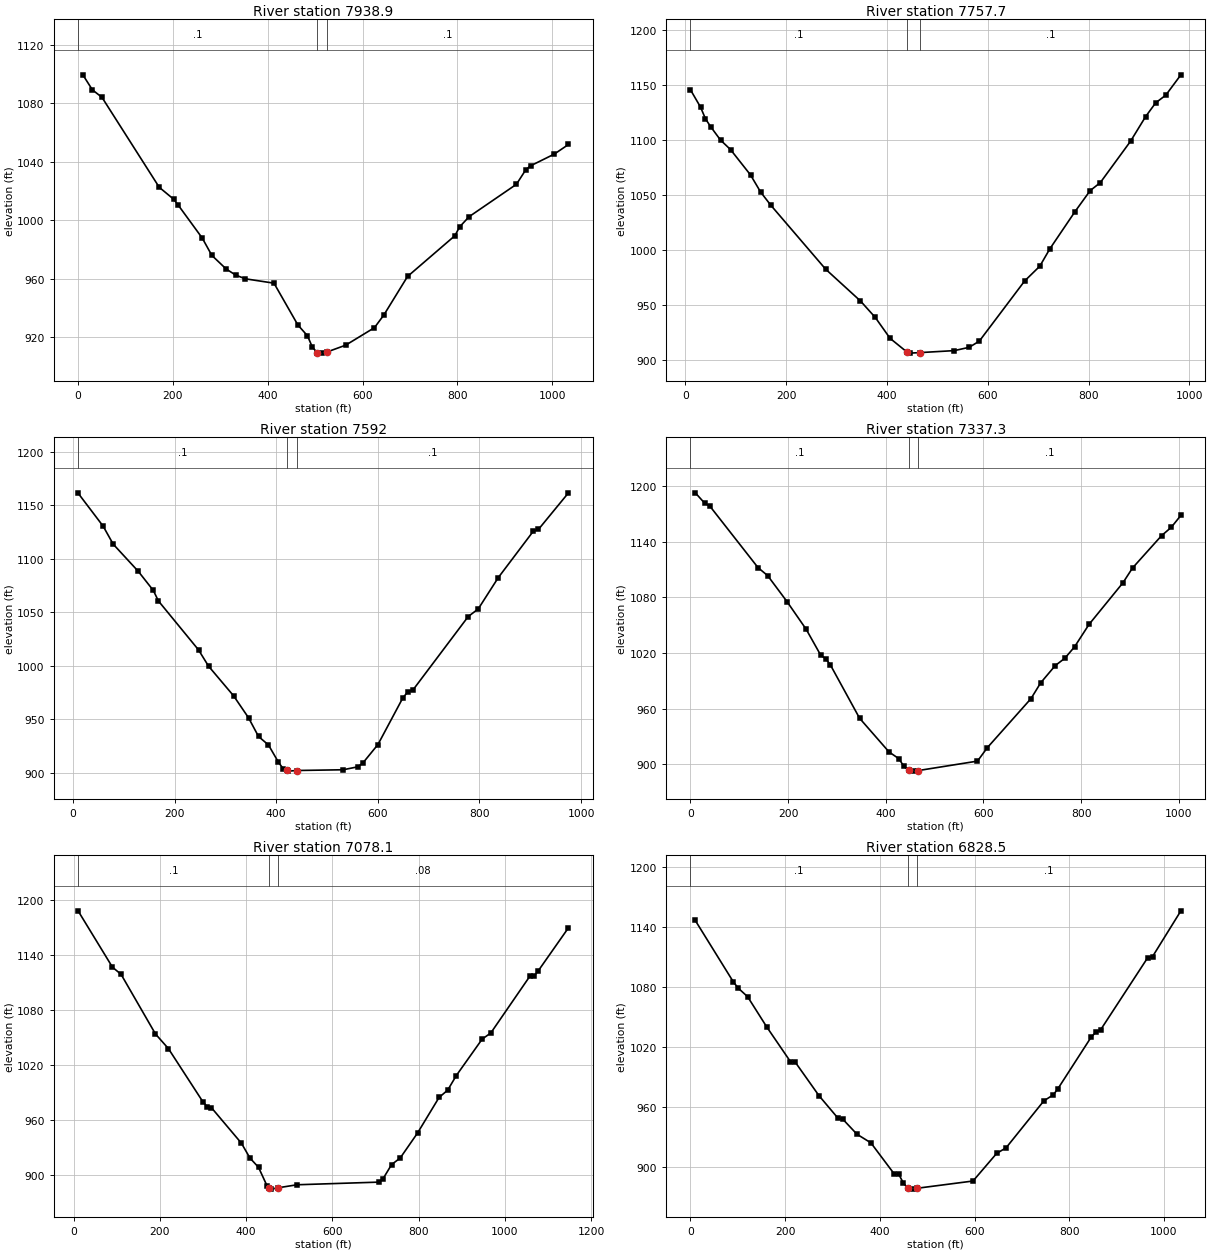
Type RM Length L Ch R = 1 ,7938.9  ,181,181.2,181.5
XS GIS Cut Line= 4
     1651585.499      209520.668     1651777.198      209779.816
     1651968.896      210014.113     1652252.893      210308.761
#Sta/Elev= 30
    10.1 1099.44    30.2 1089.17    50.4 1084.03   171.2 1022.46   201.5 1014.33
   211.5 1010.13   261.9  987.71   282.1  975.87   312.3  966.55   332.4  962.37
   352.6  959.83   413.2  956.83   463.6  928.21   483.8  920.83   493.9  913.23
   504.1  909.31   514.1  908.95   524.1  909.62   564.5  914.41   625.1  926.38
     645  935.08   694.9  961.43   794.8  989.34   804.7  995.36   824.7 1002.34
   924.5 1024.51   944.5 1034.58   954.5 1037.19  1004.4 1045.19  1034.3 1051.77
#Mann= 3 , 0 , 0
       0      .1       0   504.1    .045       0   524.1      .1       0
Bank Sta=504.1,524.1
XS Rating Curve= 0 ,0
Exp/Cntr=0.3,0.1

Type RM Length L Ch R = 1 ,7757.7  ,167.2,165.6,164.1
XS GIS Cut Line= 4
     1651417.373      209689.623     1651651.943      209903.998
     1651805.734      210095.072     1652010.789      210461.685
#Sta/Elev= 30
     9.9 1145.82    29.8 1130.11    39.7 1119.43    49.7 1112.41    69.5 1100.12
    89.4 1091.45   129.1 1068.37     149 1052.92   168.8 1041.14   278.1  982.71
   347.2   953.8   376.6  938.83   406.1  919.76  440.04  907.17   445.3  906.37
   464.9  906.84   533.6  908.66   563.1  911.68   583.1   917.3   673.1  972.02
   703.1  985.42   723.1 1001.24   773.1 1035.14   803.1 1054.16   823.1 1061.37
   883.1 1098.99   913.1 1121.45   933.1 1133.98   953.1 1140.93   983.1 1159.43
#Mann= 3 , 0 , 0
     9.9      .1       0  440.04    .045       0   464.9      .1       0
Bank Sta=440.04,464.9
XS Rating Curve= 0 ,0
Exp/Cntr=0.3,0.1

Type RM Length L Ch R = 1 ,7592    ,254.3,254.7,255.2
XS GIS Cut Line= 4
     1651245.239       209888.82     1651529.791      210026.603
     1651721.489      210236.273      1651886.23      210573.243
#Sta/Elev= 30
     9.9 1161.51    59.3  1130.6      79 1113.85   128.4 1088.42   158.1 1070.52
     168 1060.78     247 1015.03   266.8  999.77   316.2  972.01   345.5  951.55
   365.1  934.11   384.7  926.17   404.3   910.1   414.1  903.68  420.64  902.42
   423.9  901.71  440.07  902.29   531.7  902.99   561.1  905.78   570.9  909.52
   600.2  926.55   649.6  970.48   659.5     976   669.3  977.64   777.9 1046.14
   797.7 1053.32   837.1 1082.56   906.2    1126   916.1 1127.56   975.3 1161.78
#Mann= 3 , 0 , 0
     9.9      .1       0  420.64    .045       0  440.07      .1       0
Bank Sta=420.64,440.07
XS Rating Curve= 0 ,0
Exp/Cntr=0.3,0.1

Type RM Length L Ch R = 1 ,7337.3  ,249.1,259.2,269.3
XS GIS Cut Line= 4
     1651173.703      209900.514     1651326.352      210177.412
      1651539.35       210418.81     1651844.647      210621.158
#Sta/Elev= 30
     9.9 1192.42    29.6 1180.97    39.5 1178.23   138.3 1111.93   158.1 1103.26
   197.6 1075.39   237.1 1045.38   266.8 1017.55   276.7 1013.93   286.5 1007.18
   346.4   949.7   406.7  913.42   426.9  906.14   436.9  897.99     447  893.61
     457  892.79     467  893.45   587.8  903.58   607.9     918   697.5  970.94
   717.3  987.91     747 1006.39   766.8 1014.37   786.6  1026.6   816.3 1050.79
   885.6 1095.49   905.4 1111.54   964.8 1146.31   984.6 1155.25  1004.4 1168.14
#Mann= 3 , 0 , 0
       0      .1       0     447    .045       0     467      .1       0
Bank Sta=447,467
XS Rating Curve= 0 ,0
Exp/Cntr=0.3,0.1

Type RM Length L Ch R = 1 ,7078.1  ,249,249.6,250.3
XS GIS Cut Line= 4
     1651152.385       209920.27     1651143.399      210269.221
      1651231.76      210532.806     1651052.043      211021.037
#Sta/Elev= 30
      10 1188.33    89.8 1126.72   109.7 1118.95   189.5 1053.77   219.4 1037.85
   299.2  979.85   309.2   974.4   319.1  973.32   388.8  934.42   408.6  918.22
   428.5  908.05   448.4  887.63  453.93  885.86   458.3  884.22  472.74   885.6
   517.9  888.99   707.1  891.87   717.1  895.45   737.1  911.05   757.1  918.25
   797.2  945.49   847.2  984.41   867.2   992.4   887.2 1008.36   947.2 1048.19
   967.2 1054.87  1057.3 1116.58  1067.3 1116.98  1077.3 1122.83  1147.3 1169.85
#Mann= 3 , 0 , 0
      10      .1       0  453.93    .045       0  472.74     .08       0
Bank Sta=453.93,472.74
XS Rating Curve= 0 ,0
Exp/Cntr=0.3,0.1

Type RM Length L Ch R = 1 ,6828.5  ,329.2,338.8,348.4
XS GIS Cut Line= 4
     1650848.364      209989.162     1650903.906       210326.51
     1650978.658      210570.247     1651017.597      211007.559
#Sta/Elev= 30
    10.1 1146.68    90.5 1085.14   100.6 1078.94   120.7 1070.25   160.9 1040.07
   211.2 1005.14   221.2 1004.71   271.5  971.02   311.7  948.43   321.8  947.46
   351.7  932.41   381.1  923.77   430.1  892.78   439.9  892.23   449.8  883.49
   459.4  878.04   469.4  877.39   479.4   878.3   596.8  885.52   646.7  913.17
   666.7  918.83   746.5  965.89   766.5  971.93   776.4  978.23   846.3 1029.67
   856.3  1034.7   866.2 1036.95     966 1109.49     976 1110.45  1035.9 1156.31
#Mann= 3 , 0 , 0
       0      .1       0   459.4    .045       0   479.4      .1       0
Bank Sta=459.4,479.4
XS Rating Curve= 0 ,0
Exp/Cntr=0.3,0.1

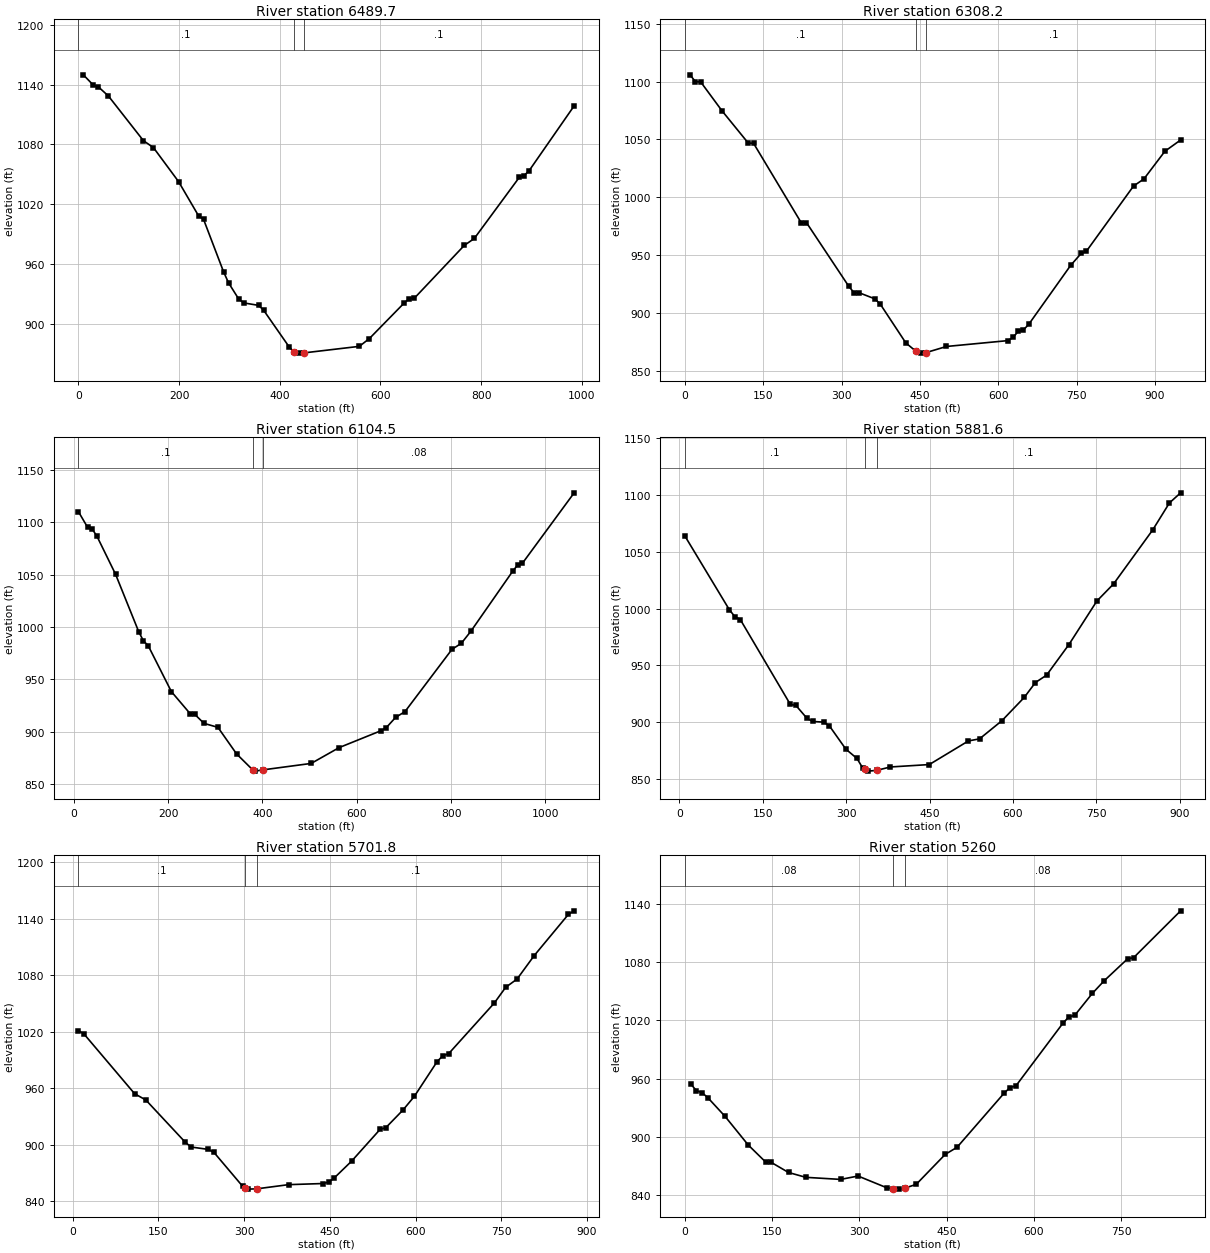
Type RM Length L Ch R = 1 ,6489.7  ,183.3,181.5,179.7
XS GIS Cut Line= 4
     1650641.689      210032.594     1650619.224      210380.046
     1650599.755      210609.186     1650716.571      210998.573
#Sta/Elev= 30
     9.9 1149.74    29.8 1139.42    39.8 1137.67    59.7 1128.54   129.3 1083.75
   149.2 1076.79     199 1042.81   238.8 1008.44   248.7 1004.92   288.5  952.29
   298.4  941.25   318.3  925.26   328.3  921.22   358.2  918.73   368.2  913.73
   418.2  877.47   428.2  871.95   438.2  870.89   448.2  871.14   558.1  877.68
   578.1  885.53   647.6  921.36   657.5  925.56   667.4  925.97   766.5  978.82
   786.4  985.77   875.6 1046.91   885.5 1048.85   895.4  1053.8   984.7 1118.67
#Mann= 3 , 0 , 0
       0      .1       0   428.2    .045       0   448.2      .1       0
Bank Sta=428.2,448.2
XS Rating Curve= 0 ,0
Exp/Cntr=0.3,0.1

Type RM Length L Ch R = 1 ,6308.2  ,204,203.6,203.3
XS GIS Cut Line= 4
     1650420.061      210025.167     1650429.382      210399.547
     1650426.275      210623.243     1650528.802      210958.787
#Sta/Elev= 30
    10.1  1105.8    20.2 1099.92    30.4  1099.7    70.9  1074.9   121.5 1046.83
   131.6 1046.67   222.7  978.17   232.8  978.21   313.8  923.19   323.9  917.62
     334  917.53   364.4  912.19   374.5  907.51   423.1  874.24   442.3  867.09
   452.3  865.42   462.3  865.95   500.9  871.17   618.3  876.22   628.3     879
   638.3  884.25   648.3  885.53   658.4  890.31   738.6  941.21   758.6  951.48
   768.6  953.34   858.9  1009.7   878.9  1015.9     919 1039.78   949.1 1049.52
#Mann= 3 , 0 , 0
       0      .1       0   442.3    .045       0   462.3      .1       0
Bank Sta=442.3,462.3
XS Rating Curve= 0 ,0
Exp/Cntr=0.3,0.1

Type RM Length L Ch R = 1 ,6104.5  ,213.7,223,232.3
XS GIS Cut Line= 3
     1650165.513      210085.113     1650225.344      210395.023
     1649900.356       211019.54
#Sta/Elev= 30
     9.9 1110.47    29.6 1095.29    39.5 1093.55    49.3 1086.87    88.8 1050.48
   138.1  995.32     148  986.71   157.8  982.35   207.1  938.27   246.6  917.32
   256.5  916.61   276.2  907.91   305.8  904.09   345.3  878.71  380.13  863.17
   384.8  862.24  400.28  863.39   503.4   869.6   562.7  884.73   652.4  901.07
   662.4  903.71   682.3  913.59   702.2  919.13   801.8  978.66   821.7  984.48
   841.7  995.86   931.3 1053.87   941.3 1059.43   951.2 1061.02  1060.8 1128.33
#Mann= 3 , 0 , 0
     9.9      .1       0  380.13    .045       0  400.28     .08       0
Bank Sta=380.13,400.28
XS Rating Curve= 0 ,0
Exp/Cntr=0.3,0.1

Type RM Length L Ch R = 1 ,5881.6  ,180.2,179.7,179.3
XS GIS Cut Line= 4
     1650087.624       210112.16     1650033.254      210376.245
     1649968.009      210544.017     1649703.923       210910.63
#Sta/Elev= 30
      10 1063.93    89.9  999.17    99.9  992.94   109.8  990.38   199.7  915.83
   209.7  914.94   229.7  903.57   239.7  900.85   259.6  900.22   269.6   897.2
   299.6  876.48   319.6   868.3   329.6  860.15  334.51  858.63   339.6  857.18
  354.73  857.81   379.6  860.83   449.6  862.95   519.9   883.7     540  885.55
   580.2   901.5   620.3  921.93   640.4  935.02   660.5  941.53   700.7  968.44
   750.9 1006.64     781 1021.72   851.3 1069.12   881.4 1092.88   901.5 1101.73
#Mann= 3 , 0 , 0
      10      .1       0  334.51    .045       0  354.73      .1       0
Bank Sta=334.51,354.73
XS Rating Curve= 0 ,0
Exp/Cntr=0.3,0.1

Type RM Length L Ch R = 1 ,5701.8  ,446.2,441.9,437.5
XS GIS Cut Line= 4
      1649942.29      210091.002     1649880.887      210267.723
      1649783.54      210531.308      1649573.87      210883.254
#Sta/Elev= 30
     9.8 1021.26    19.7 1017.61   108.3  954.11     128  947.41   197.1  902.44
   207.2  897.43   237.3  894.91   247.3  891.64   297.5   855.6   302.1  854.23
   307.5  852.67  322.27     853   377.8  857.43     438  858.63     448  860.17
     458  864.71   488.1  882.39     538   916.2     548  917.99     578  936.72
     598  951.33   637.9  988.29   647.9  994.58   657.9  996.59   737.9 1050.49
   757.8  1067.2   777.8 1076.03   807.8 1100.98   867.7 1144.82   877.7 1148.54
#Mann= 3 , 0 , 0
     9.8      .1       0   302.1    .045       0  322.27      .1       0
Bank Sta=302.1,322.27
XS Rating Curve= 0 ,0
Exp/Cntr=0.3,0.1

Type RM Length L Ch R = 1 ,5260    ,333.3,312.2,291
XS GIS Cut Line= 4
     1649534.931      210026.603     1649428.599      210216.804
     1649388.163      210442.948     1649398.646      210847.311
#Sta/Elev= 30
     9.9  954.82    19.8  947.63    29.7  945.54    39.6  940.36    69.3  921.04
     109  891.64   138.7  874.24   148.6   873.7   178.3  863.32     208  858.33
   267.8  856.19   297.8  859.67   347.8  847.41   357.7  846.51   367.7  846.18
   377.7  847.12   397.7   851.1   447.6  881.99   467.9  889.29   548.8  945.07
   558.9  950.84     569  952.53   649.9 1017.16     660 1023.59   670.1 1025.19
   700.4 1047.83   720.7 1060.82   761.1  1083.5   771.2 1084.57   852.1 1132.87
#Mann= 3 , 0 , 0
       0     .08       0   357.7    .045       0   377.7     .08       0
Bank Sta=357.7,377.7
XS Rating Curve= 0 ,0
Exp/Cntr=0.3,0.1

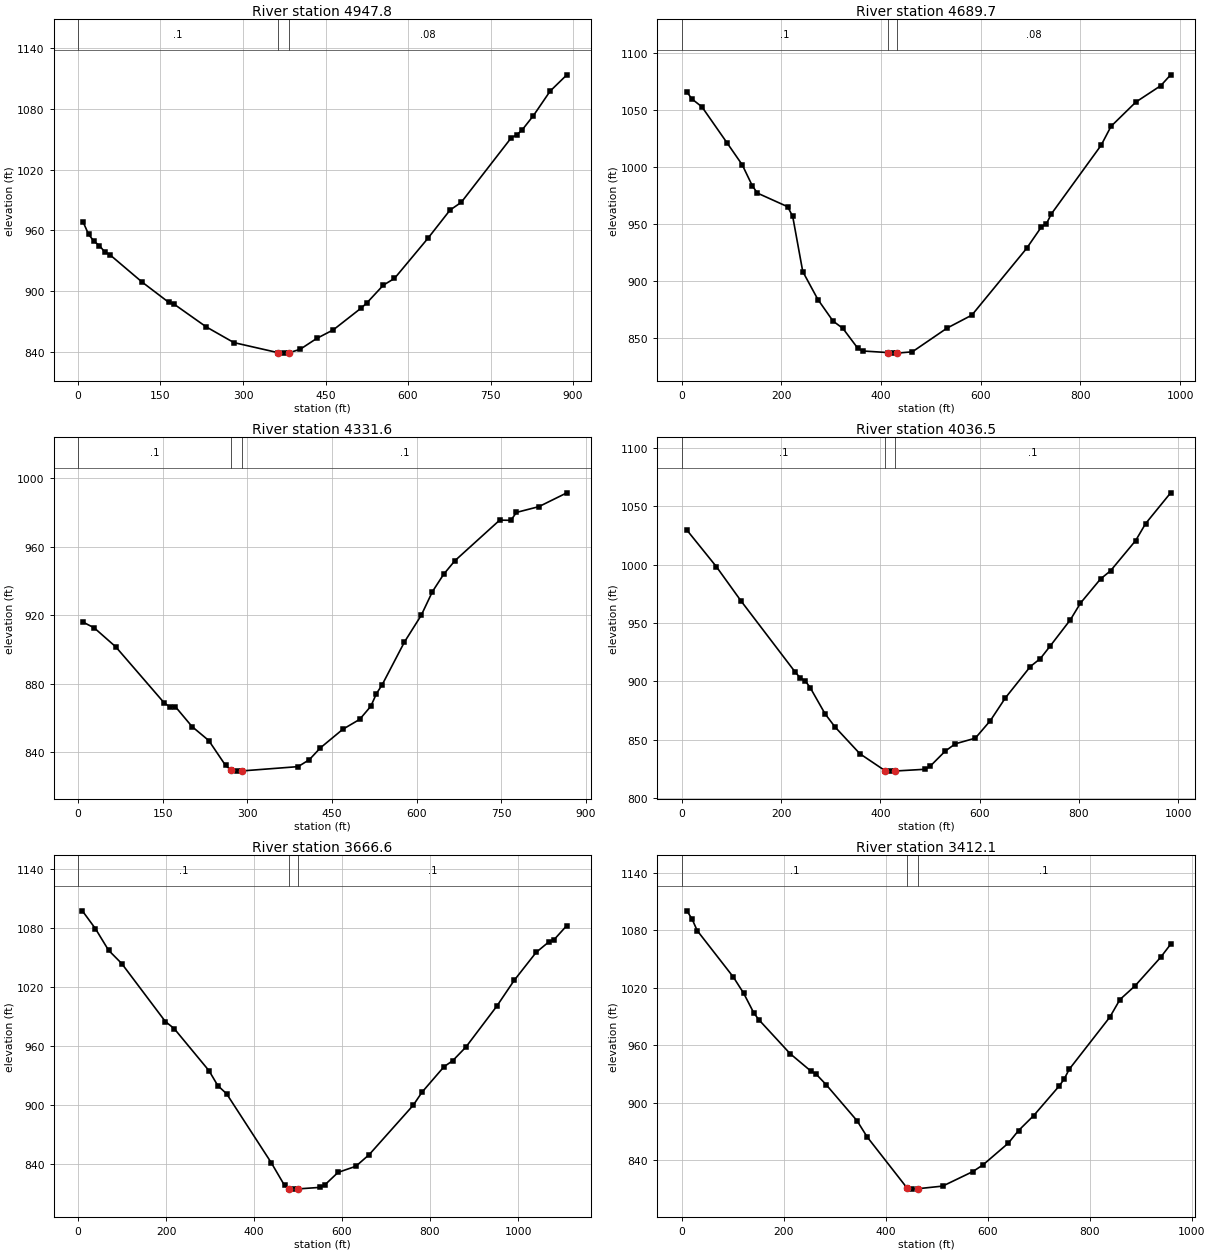
Type RM Length L Ch R = 1 ,4947.8  ,255.9,258.1,260.3
XS GIS Cut Line= 4
     1648948.372       210055.02     1649065.345      210256.799
     1649201.326      210430.796      1649359.24      210835.816
#Sta/Elev= 30
     9.7  967.76    19.4  955.88    29.2   949.1    38.9  944.94    48.6   938.6
    58.3   935.7   116.6  908.78   165.2  888.67   174.9  886.88   233.2  864.47
   283.4  848.94   363.8  838.96   373.8  838.52   383.8  838.91   403.9  842.32
     434  853.05   464.2  861.55   514.7  883.03   524.8  887.99   555.2  905.78
   575.4  912.42     636  951.97   676.5  980.08   696.7  987.62   787.7 1051.53
   797.8 1054.44   807.9 1059.58   828.1 1073.53   858.4  1097.7   888.8  1113.8
#Mann= 3 , 0 , 0
       0      .1       0   363.8    .045       0   383.8     .08       0
Bank Sta=363.8,383.8
XS Rating Curve= 0 ,0
Exp/Cntr=0.3,0.1

Type RM Length L Ch R = 1 ,4689.7  ,364.8,358.2,351.6
XS GIS Cut Line= 4
     1648676.523      210147.126     1648860.234      210388.746
     1649000.014      210606.403     1649274.471      210922.905
#Sta/Elev= 30
    10.1 1066.26    20.2 1059.97    40.5 1052.99    91.1 1021.27   121.4 1002.13
   141.6  983.75   151.8  977.37   212.5  965.41   222.6  956.96   242.8  908.56
   273.2  884.03   303.5  865.16   323.4  858.67   353.3  841.24   363.2  838.88
   412.9  837.53   422.9  837.01   432.9  837.07   462.7  838.15   532.4  858.96
   582.2  870.36   691.9   928.8   721.8  947.74   731.8   950.5   741.7   959.1
   841.5 1019.26   861.4 1035.89   911.3 1057.21   961.2 1071.56   981.1 1081.09
#Mann= 3 , 0 , 0
       0      .1       0   412.9    .045       0   432.9     .08       0
Bank Sta=412.9,432.9
XS Rating Curve= 0 ,0
Exp/Cntr=0.3,0.1

Type RM Length L Ch R = 1 ,4331.6  ,294.9,295,295.1
XS GIS Cut Line= 4
     1648414.196      210453.681      1648532.01      210565.505
     1648751.665       210765.19     1649099.117      210976.857
#Sta/Elev= 30
     9.6  915.77    28.7  912.54    66.9  901.45   152.9  868.63   162.4  866.47
   172.3  866.58     202  854.88   231.7  846.71   261.4  832.19   271.2  829.43
   281.2  828.84   291.2  828.98     390  831.47   409.8  835.51   429.6  842.48
   469.2  853.29     499  859.07   518.8  866.73   528.8  874.17   538.7  879.18
   578.4  904.29   608.1  919.87     628  933.74   647.8  943.82   667.7  951.74
   747.1  975.47   766.9  975.35   776.8  979.97   816.5  983.34   866.1  991.41
#Mann= 3 , 0 , 0
       0      .1       0   271.2    .045       0   291.2      .1       0
Bank Sta=271.2,291.2
XS Rating Curve= 0 ,0
Exp/Cntr=0.3,0.1

Type RM Length L Ch R = 1 ,4036.5  ,369.2,370,370.8
XS GIS Cut Line= 4
     1648200.532      210547.533     1648382.246      210821.102
     1648575.941      210998.822     1648813.567      211312.329
#Sta/Elev= 30
      10  1029.7    69.7  998.24   119.4  968.88   228.9  907.82   238.9  902.97
   248.8  900.48   258.8  894.65   288.6  872.37   308.5  861.18   358.8  838.18
   409.4  823.72   419.4  823.32   429.4  823.41   490.2  824.91   500.3  827.51
   530.6  840.42   550.9  846.67   591.3  851.52   621.6  866.55   651.8  885.97
   702.2  912.83   722.4  919.67   742.6  930.64   782.9  952.91   803.1  967.08
   843.5  987.73   863.6   994.7   914.1 1020.49   934.2 1035.05   984.7 1061.41
#Mann= 3 , 0 , 0
       0      .1       0   409.4    .045       0   429.4      .1       0
Bank Sta=409.4,429.4
XS Rating Curve= 0 ,0
Exp/Cntr=0.3,0.1

Type RM Length L Ch R = 1 ,3666.6  ,257.6,254.4,251.2
XS GIS Cut Line= 4
     1647946.783      210731.207      1648074.73      211032.769
     1648328.331      211280.379     1648674.527      211533.499
#Sta/Elev= 30
     9.9 1097.85    39.7 1079.64    69.5 1057.69    99.3 1044.22   198.5  985.17
   218.4  978.05   297.8  935.05   317.7  919.91   337.7  911.62     439  841.57
   469.4  818.28   479.6  814.59   489.6  814.55   499.6  814.75   550.4  816.35
   560.5  818.67   590.9  831.57   631.4  837.82   661.8  849.72   761.8  899.96
   781.8  913.26   831.6  939.11   851.6  945.32   881.5  959.19   951.3 1000.57
   991.2 1027.07  1041.1 1055.57    1071 1066.62    1081 1068.09  1110.9  1082.9
#Mann= 3 , 0 , 0
       0      .1       0   479.6    .045       0   499.6      .1       0
Bank Sta=479.6,499.6
XS Rating Curve= 0 ,0
Exp/Cntr=0.3,0.1

Type RM Length L Ch R = 1 ,3412.1  ,224.4,236.8,249.3
XS GIS Cut Line= 4
     1647674.607      211051.541     1647944.906      211279.897
     1648110.348      211404.561     1648440.067      211627.092
#Sta/Elev= 30
    10.1 1100.47    20.2 1091.86    30.3 1079.76   101.1 1031.26   121.3 1014.37
   141.5  993.49   151.6  986.35   212.3  951.21   252.7  933.14   262.9  930.04
   283.1  918.73   343.7     881   363.7  863.96   442.5   810.2   452.5  809.47
   462.5  809.87   511.7  812.64   570.9  827.83   590.8  834.82   640.6  857.63
   660.4  870.68   690.3  886.42     740  917.16   749.9   924.5   759.9  934.81
   839.5   989.3   859.3 1007.67   889.2 1022.14   938.9 1051.68   958.8 1065.54
#Mann= 3 , 0 , 0
       0      .1       0   442.5    .045       0   462.5      .1       0
Bank Sta=442.5,462.5
XS Rating Curve= 0 ,0
Exp/Cntr=0.3,0.1

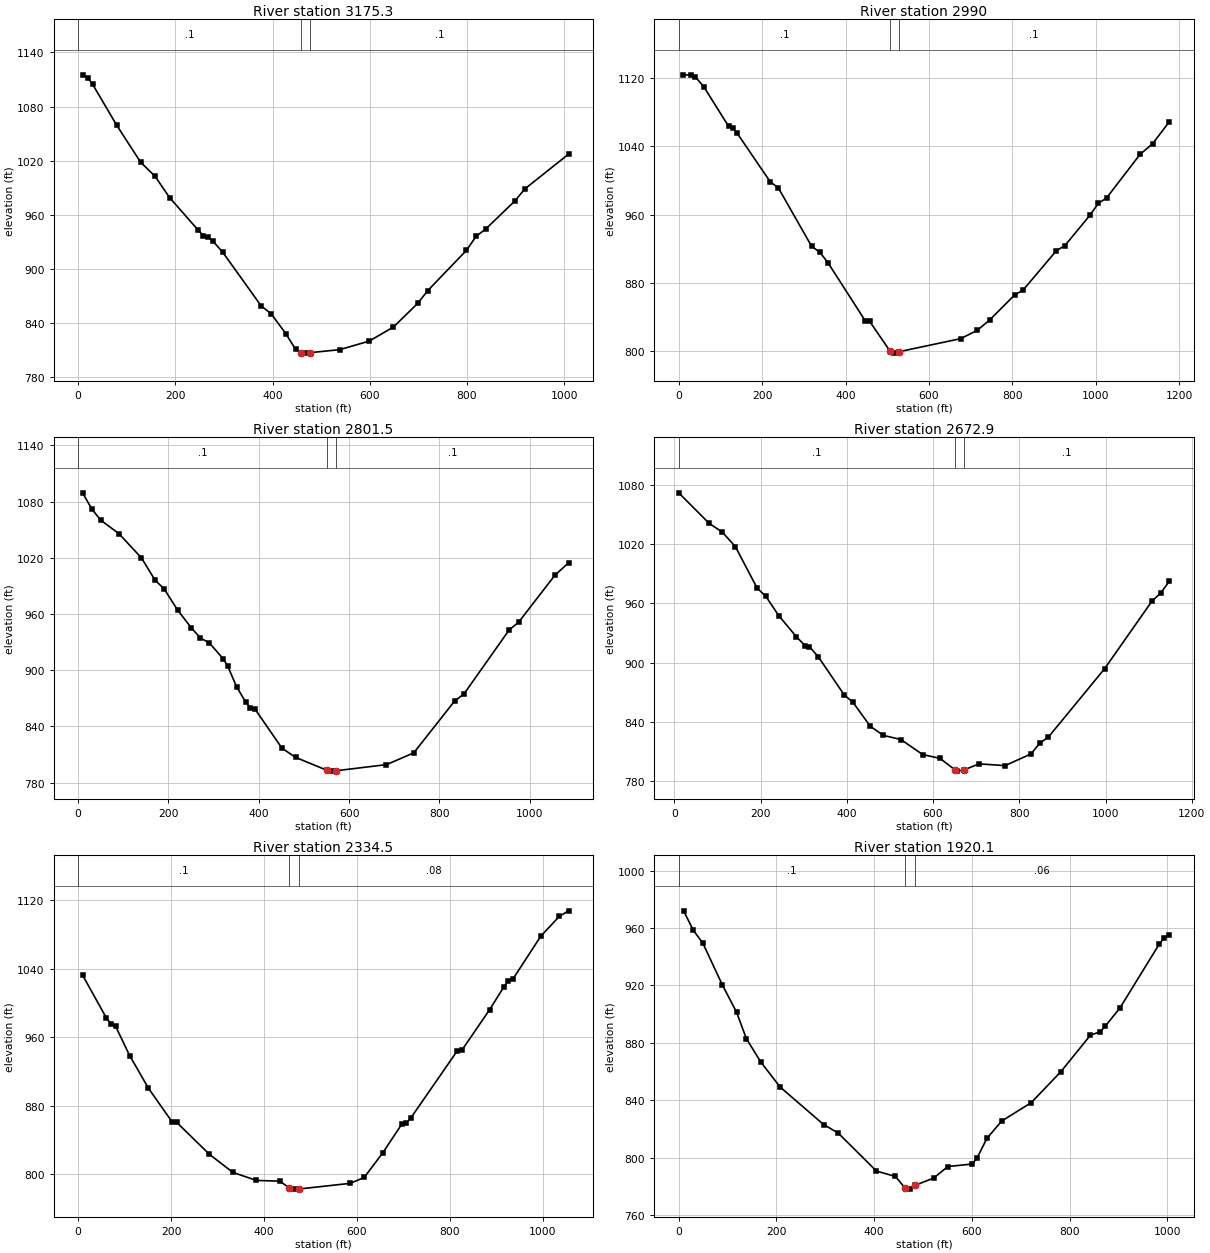
Type RM Length L Ch R = 1 ,3175.3  ,187.2,185.3,183.4
XS GIS Cut Line= 4
     1647633.181      211073.742       1647799.4      211389.091
     1647895.714       211600.36     1648225.044      211861.339
#Sta/Elev= 30
     9.9 1115.22    19.8 1111.84    29.7  1104.9    79.2  1059.5   128.7 1018.21
   158.4  1002.6   188.1  979.08   247.6  942.52   257.5  936.75   267.4  935.23
   277.3  930.63   297.1  918.68   376.7  858.73   396.9  850.26   427.1  828.13
   447.3  810.67   457.5  806.74   467.5  806.42   477.5  806.96   538.2  810.27
   598.7  819.77   648.7   835.4   698.7  861.74   718.7  875.52   798.8   920.5
   818.8  936.09   838.8  944.38   898.8  975.49   918.8  988.63  1008.9 1027.26
#Mann= 3 , 0 , 0
       0      .1       0   457.5    .045       0   477.5      .1       0
Bank Sta=457.5,477.5
XS Rating Curve= 0 ,0
Exp/Cntr=0.3,0.1

Type RM Length L Ch R = 1 ,2990    ,187.8,188.5,189.2
XS GIS Cut Line= 4
     1647598.887      211057.804     1647595.337       211416.35
     1647781.192      211755.631     1647783.485      212186.693
#Sta/Elev= 30
      10 1123.49    29.9 1123.67    39.8 1121.18    59.8 1109.95   119.5 1063.46
   129.5 1061.14   139.4  1055.8   219.1   998.7     239   991.2   318.7  922.92
   338.6  915.94   358.6  903.16   447.8  835.35   457.8   835.1   507.3  799.84
   517.3  797.89   527.3  799.47     676   814.8   715.7  824.52   745.4  836.54
   805.6  866.05   825.6  871.54   905.8  917.89   925.9  923.66     986  959.21
  1006.1   973.1  1026.1  979.57  1106.3 1030.55  1136.4    1043  1176.5 1068.73
#Mann= 3 , 0 , 0
       0      .1       0   507.3    .045       0   527.3      .1       0
Bank Sta=507.3,527.3
XS Rating Curve= 0 ,0
Exp/Cntr=0.3,0.1

Type RM Length L Ch R = 1 ,2801.5  ,126.7,128.5,130.3
XS GIS Cut Line= 4
     1647553.438      211100.474     1647470.717      211574.663
     1647572.079      211771.563     1647696.743      212133.903
#Sta/Elev= 30
      10 1089.35    30.1 1072.32    50.1 1060.18    90.3 1045.86   140.4 1019.85
   170.5  996.11   190.5  986.87   220.6  964.06   250.7  945.28   270.8  934.42
   290.8  929.09   320.9  912.46   330.9  904.75     351  882.34     371  866.04
   381.1   860.1   391.1  858.97   451.3  816.86   481.4  807.04   551.9  793.05
   561.9  792.34   571.9  792.79   682.7  799.27   743.1  811.82   833.9  867.33
   854.1  874.56   954.9  943.37   975.1  951.16  1055.7 1001.48    1086 1014.66
#Mann= 3 , 0 , 0
       0      .1       0   551.9    .045       0   571.9      .1       0
Bank Sta=551.9,571.9
XS Rating Curve= 0 ,0
Exp/Cntr=0.3,0.1

Type RM Length L Ch R = 1 ,2672.9  ,339.6,338.4,337.3
XS GIS Cut Line= 4
     1647518.375      211079.997      1647375.18      211658.549
      1647446.25      211825.156     1647640.819      212140.894
#Sta/Elev= 30
    10.1 1071.78    80.8 1040.81   111.1 1032.07   141.4 1017.37   191.9  975.38
   212.1  967.04   242.4  947.34   282.9  926.17   303.1   917.1   313.2  916.05
   333.4   906.1     394  867.27   414.2  859.78   454.6  835.48   484.9   826.3
   525.3  822.17   575.8  806.99   616.1  803.05  650.53   791.6   656.4  790.17
  671.72  791.43   706.7  797.51   767.1  795.76   827.3  807.59   847.3  818.42
   867.4  824.55   997.7  893.69  1107.9  962.26    1128  970.33    1148  982.27
#Mann= 3 , 0 , 0
    10.1      .1       0  650.53    .045       0  671.72      .1       0
Bank Sta=650.53,671.72
XS Rating Curve= 0 ,0
Exp/Cntr=0.3,0.1

Type RM Length L Ch R = 1 ,2334.5  ,414.6,414.4,414.3
XS GIS Cut Line= 4
     1646846.294       211458.95     1647048.642      211760.697
     1647185.001      212042.102     1647311.339      212399.691
#Sta/Elev= 30
    10.1  1032.1    60.6   982.8    70.6  975.63    80.7  972.79     111  938.59
   151.4  900.42   201.8  861.43   211.9  860.68   282.6  823.19     333  802.12
   383.5  792.73   433.9  791.89   454.2  784.01   464.2  782.57   474.2  782.65
   585.2  789.32   615.5  796.19   655.8  825.22     696  858.15     706  859.55
   715.9  865.77   815.7  944.05   825.7  944.89   885.6  992.38   915.5  1018.4
   925.5  1025.5   935.5 1027.98   995.4    1078  1035.3  1101.2  1055.3 1107.64
#Mann= 3 , 0 , 0
       0      .1       0   454.2    .045       0   474.2     .08       0
Bank Sta=454.2,474.2
XS Rating Curve= 0 ,0
Exp/Cntr=0.3,0.1

Type RM Length L Ch R = 1 ,1920.1  ,218.4,214,209.5
XS GIS Cut Line= 4
     1646473.251      211649.798     1646682.921      211949.326
      1646772.78      212133.037     1647050.343      212466.512
#Sta/Elev= 30
     9.9  972.04    29.6   958.6    49.4  949.47    88.9  920.64   118.6   901.2
   138.3     883     168  866.64   207.5  849.23   296.4  823.09   326.1  817.24
   404.6  790.67   443.5  786.89   462.7  779.03   472.7  778.07   482.7  780.61
   521.4  785.71   550.7   793.8   600.4  795.57   610.5  799.72   630.7  813.46
   660.9   825.5   721.5  838.38     782  859.89   842.6  885.39   862.7  887.76
   872.8  891.59   903.1   904.4   983.8  949.05   993.9  953.38    1004  955.03
#Mann= 3 , 0 , 0
       0      .1       0   462.7    .045       0   482.7     .06       0
Bank Sta=462.7,482.7
XS Rating Curve= 0 ,0
Exp/Cntr=0.3,0.1