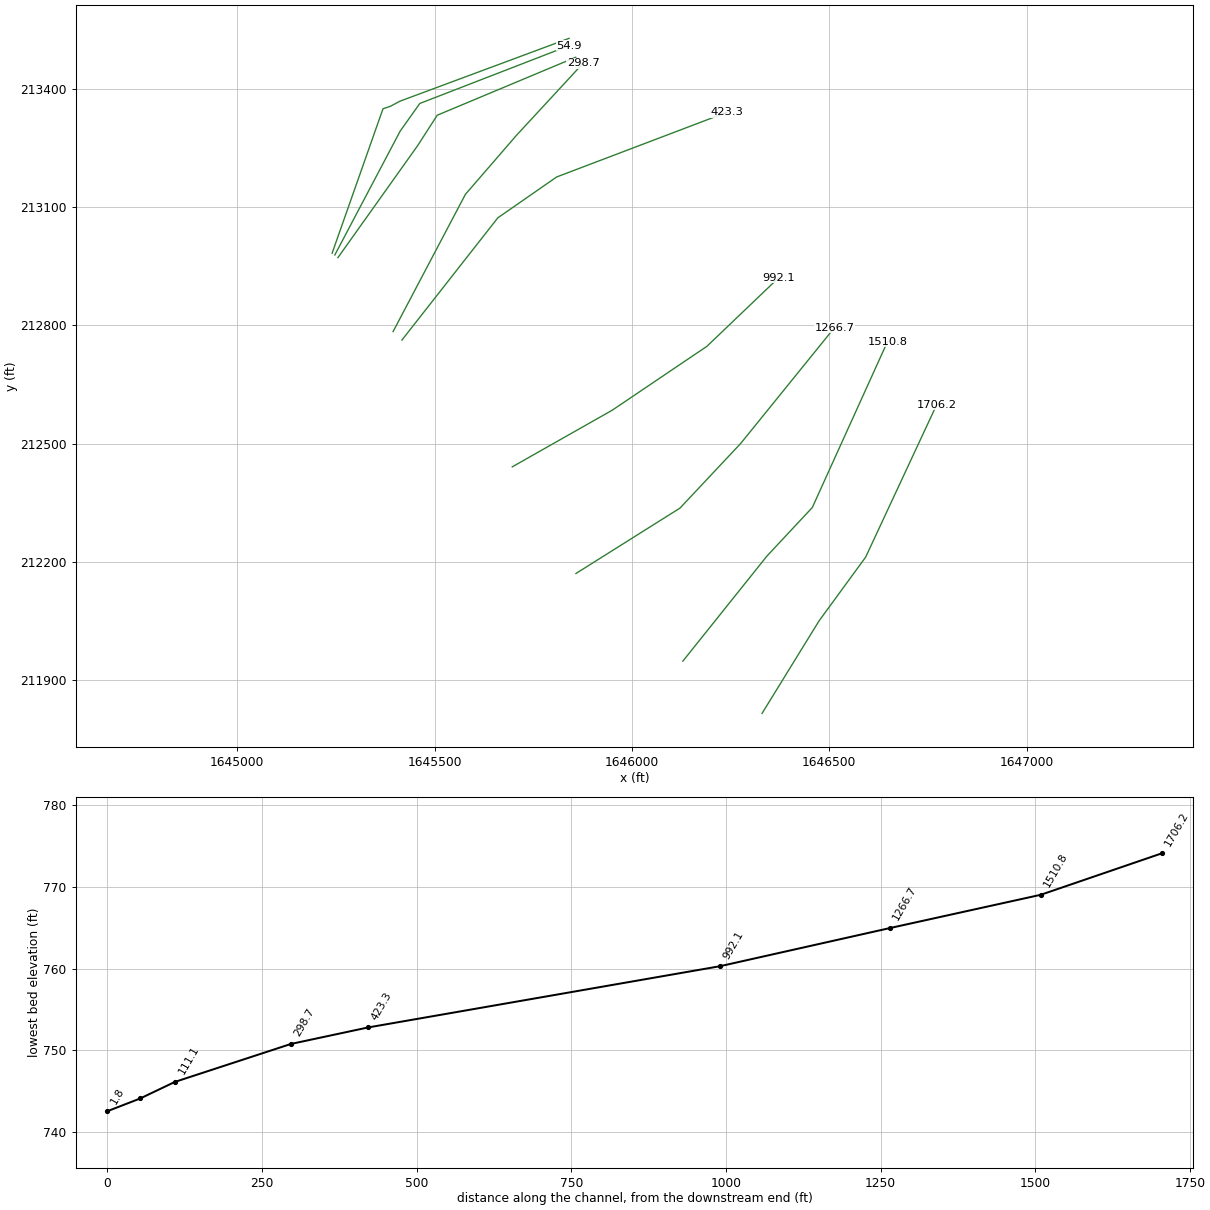
HEC-RAS study cnlyfrk.prj: cnlyfrk

--- cnlyfrk.g01 (geometry) --- (continued)

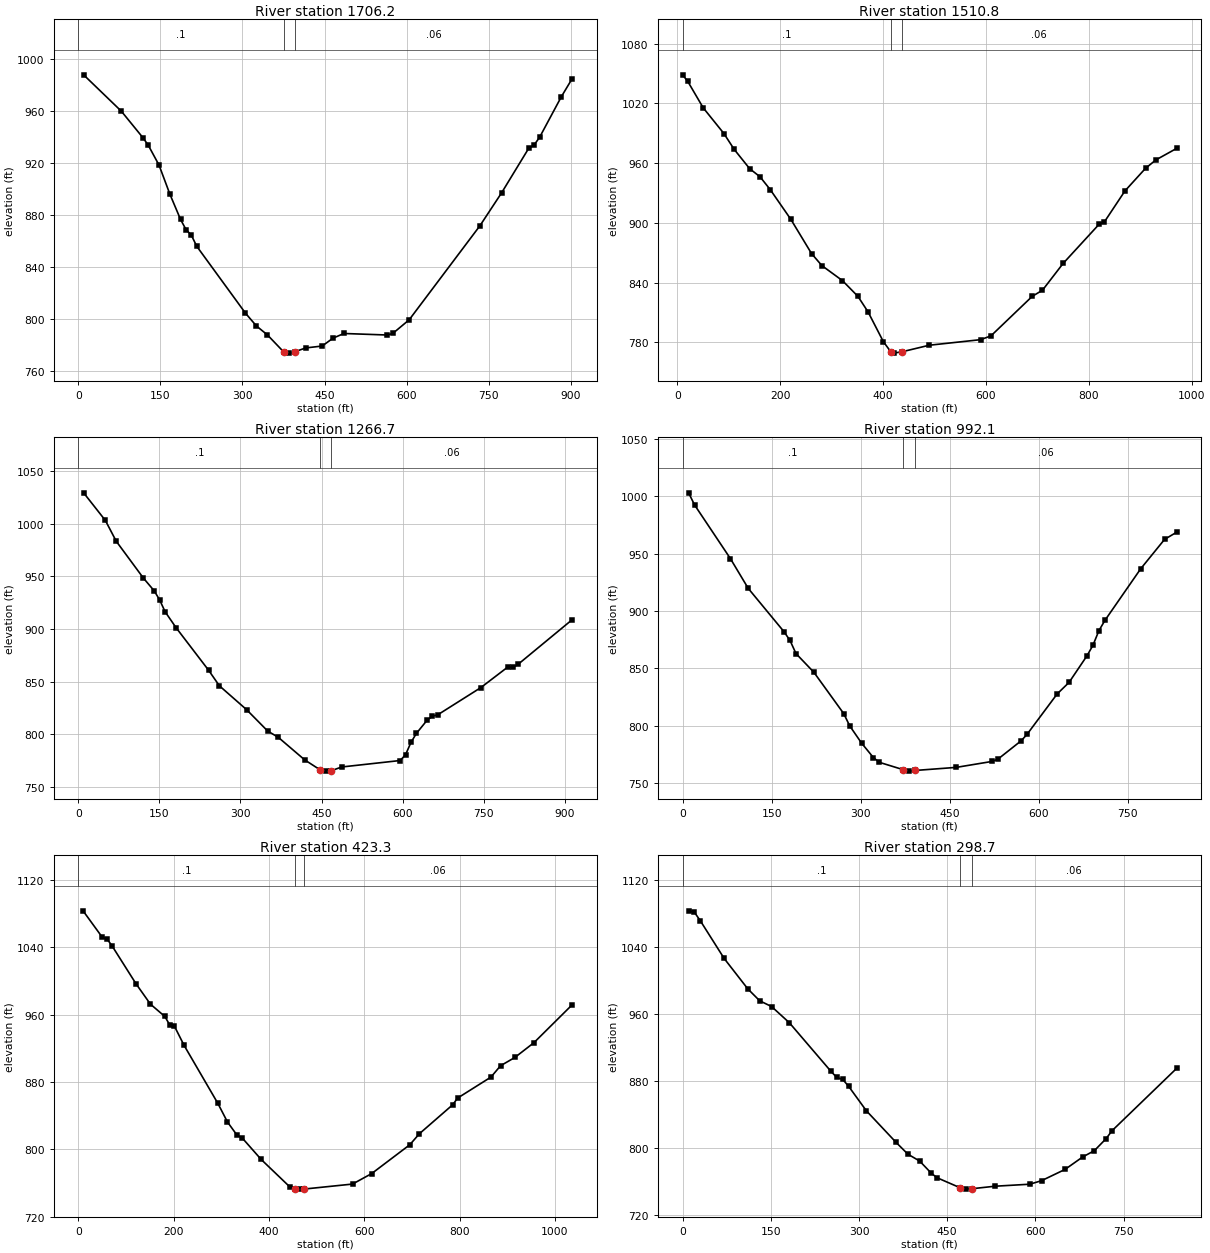
Type RM Length L Ch R = 1 ,1706.2  ,198.4,195.4,192.4
XS GIS Cut Line= 4
     1646329.841      211816.289     1646474.312      212050.859
     1646592.373      212212.417     1646772.573      212599.225
#Sta/Elev= 30
     9.8  988.11    78.7  960.16   118.1   939.8   127.9  933.98   147.6  918.69
   167.3  896.46   186.9  876.91   196.8  869.17   206.6  864.82   216.5  856.26
   305.5  804.84   325.5  794.99   345.5  788.16   375.5  774.95   385.5  774.11
   395.5  775.17   415.6   778.1   445.6  779.57   465.6  785.67   485.5  789.21
   564.9  788.03   574.8  789.31   604.6  799.76   733.6  871.93   773.3   897.3
   822.9  931.59   832.8  934.18   842.8  940.06   882.5  971.24   902.3  985.16
#Mann= 3 , 0 , 0
       0      .1       0   375.5    .045       0   395.5     .06       0
Bank Sta=375.5,395.5
XS Rating Curve= 0 ,0
Exp/Cntr=0.3,0.1

Type RM Length L Ch R = 1 ,1510.8  ,244.1,244.1,244
XS GIS Cut Line= 4
       1646129.2      211948.845     1646342.198      212215.093
     1646457.224      212338.246     1646647.495      212758.238
#Sta/Elev= 30
      10 1048.65    20.1 1041.97    50.1 1015.48    90.3  989.68   110.3  973.76
   140.4  954.36   160.5  946.24   180.5  933.27   220.6  903.38   260.7  869.12
   280.8     857   320.9  841.87   350.9  826.12   370.7  810.44   400.4   780.6
  414.48  770.66   420.3  769.04  436.07  770.31   489.7  776.98   589.7  782.57
   609.7  786.39   689.9  826.07   709.9  832.26     750  859.14   820.2  898.62
   830.2   900.8   870.3  932.02   910.4  954.78   930.5  963.18   970.6  974.66
#Mann= 3 , 0 , 0
      10      .1       0  414.48    .045       0  436.07     .06       0
Bank Sta=414.48,436.07
XS Rating Curve= 0 ,0
Exp/Cntr=0.3,0.1

Type RM Length L Ch R = 1 ,1266.7  ,280.2,274.6,269
XS GIS Cut Line= 4
      1645858.22      212170.977     1646121.805      212336.716
     1646275.563      212500.458     1646513.188      212793.996
#Sta/Elev= 30
      10 1029.53    50.2 1003.26    70.3  983.49   120.5   948.5   140.6  936.31
   150.7   927.6   160.7  916.47   180.8  901.44   241.1  860.88   261.1  846.07
   311.4  823.39   350.4  803.08     370   797.1   418.8  775.68   447.9  766.02
   457.9  764.96   467.9  765.33   487.2  768.89   595.6  775.05   605.5  780.64
   615.5  792.28   625.4  800.78   645.3  813.38   655.2  817.17   665.2  818.58
   744.7  844.37   794.4  863.87   804.3  863.51   814.3   866.8   913.6  908.93
#Mann= 3 , 0 , 0
       0      .1       0   447.9    .045       0   467.9     .06       0
Bank Sta=447.9,467.9
XS Rating Curve= 0 ,0
Exp/Cntr=0.3,0.1

Type RM Length L Ch R = 1 ,992.1   ,568.5,568.8,569.1
XS GIS Cut Line= 4
      1645696.77      212441.292     1645950.371      212585.066
     1646189.993      212746.811     1646371.707      212920.538
#Sta/Elev= 30
    10.1 1002.89    20.1  992.37    80.4  945.64   110.6  919.55   170.9  881.75
   180.9   874.2     191  862.76   221.2  846.41   271.4  810.42   281.5  799.74
   301.5  784.69   321.4   772.1   331.4  767.96   371.2  761.62   381.2  760.29
   391.2  760.85     461  763.56   520.8   768.7   530.8  770.59   570.7  786.92
   580.6  792.62   630.9  827.57     651  837.67   681.2  860.86   691.2  869.99
   701.3   882.8   711.4  891.71   771.7  936.73   811.9  962.34     832  968.48
#Mann= 3 , 0 , 0
       0      .1       0   371.2    .045       0   391.2     .06       0
Bank Sta=371.2,391.2
XS Rating Curve= 0 ,0
Exp/Cntr=0.3,0.1

Type RM Length L Ch R = 1 ,423.3   ,118.4,124.6,130.9
XS GIS Cut Line= 4
      1645417.21      212762.786     1645660.212      213072.624
     1645809.321      213176.242     1646239.915      213339.878
#Sta/Elev= 30
    10.1 1083.44    50.5 1051.95    60.6 1049.79    70.7    1042   121.2  996.74
   151.4  972.58   181.7   957.9   191.8  947.98   201.9  946.18   222.1  923.51
   292.8  854.72     313  832.56   333.2  816.76   343.3  813.98   383.7  788.05
   444.2  755.23   454.4  753.24   464.4  752.79   474.4   752.9   575.3   758.8
   615.4  771.23   695.5  805.54   715.5  818.56   785.6   853.1   795.6  860.93
   865.7  885.91   885.8  899.39   915.8   909.2   955.9  926.82    1036  971.79
#Mann= 3 , 0 , 0
       0      .1       0   454.4    .045       0   474.4     .06       0
Bank Sta=454.4,474.4
XS Rating Curve= 0 ,0
Exp/Cntr=0.3,0.1

Type RM Length L Ch R = 1 ,298.7   ,184.1,187.6,191.2
XS GIS Cut Line= 4
     1645394.668      212784.085     1645577.974      213132.056
      1645706.91      213281.187     1645876.235      213464.494
#Sta/Elev= 30
    10.1 1083.69    20.2 1081.83    30.3 1071.61    70.6 1026.78   110.9   990.3
   131.1  976.08   151.3  969.18   181.5  949.84   252.1  891.84   262.2  884.32
   272.3  882.03   282.4  873.71   312.6  844.42     363  806.72   383.2  792.55
   403.2  784.33   422.9  769.84   432.7  764.41     472  752.41     482  750.77
     492  751.25   531.3  754.25   590.4  756.65   610.4  760.86   650.3  774.31
   680.3  789.21   700.2  796.76   720.2  811.13   730.2  820.56     840   895.1
#Mann= 3 , 0 , 0
       0      .1       0     472    .045       0     492     .06       0
Bank Sta=472,492
XS Rating Curve= 0 ,0
Exp/Cntr=0.3,0.1

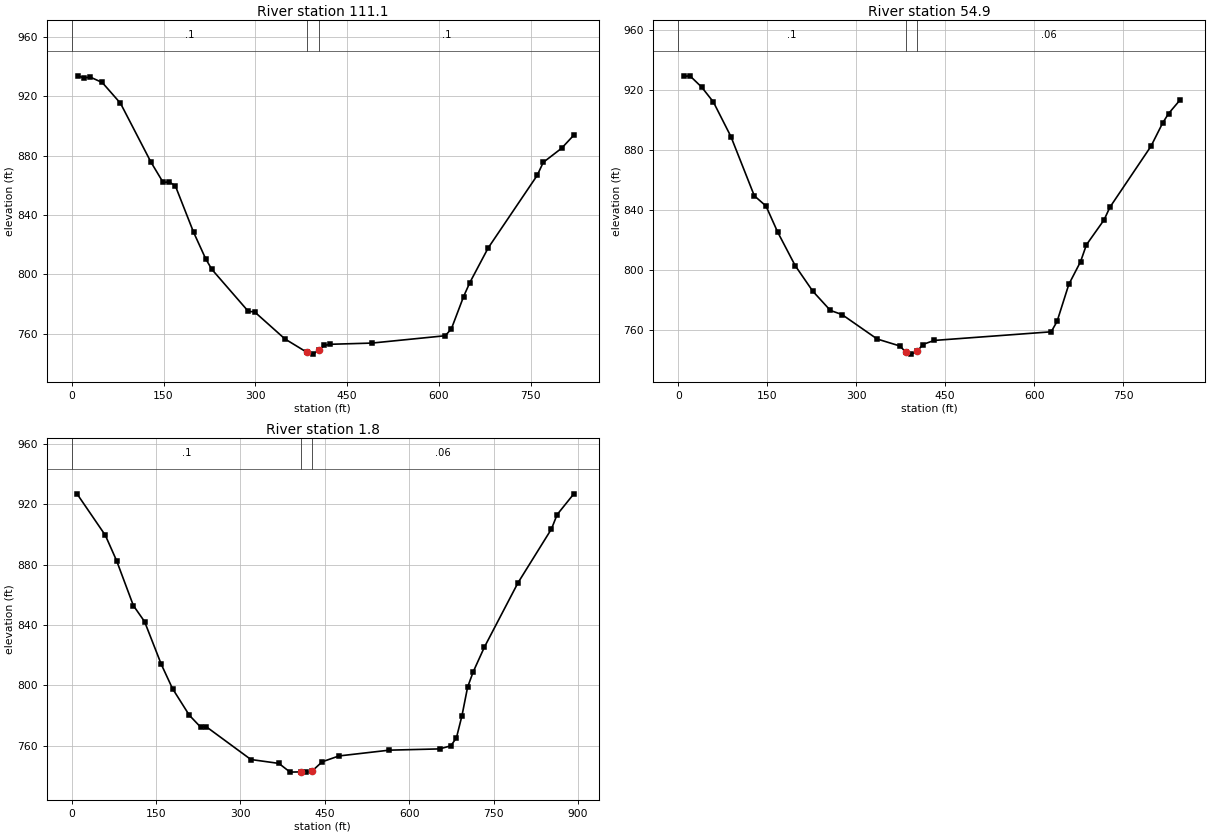
Type RM Length L Ch R = 1 ,111.1   ,57.3,56.1,55
XS GIS Cut Line= 4
     1645254.927      212971.671     1645456.937      213255.572
     1645506.693      213332.812     1645857.615      213479.683
#Sta/Elev= 30
      10  933.86    19.9  932.41    29.9  933.06    49.8  929.36    79.6  915.36
   129.4  875.67   149.3  861.98   159.3  862.22   169.2  859.77   199.1  828.34
     219  810.34     229  803.28   288.7  774.91   298.7  774.68   348.4  756.38
   384.4  747.34   394.4  746.12   404.4   748.9   412.8  751.95   421.9  752.75
   490.4  753.57   610.5  758.53   620.5  763.17   640.5  784.97   650.5  794.24
   680.6  817.71   760.7  866.64   770.7  875.49   800.7  885.01   820.7  893.88
#Mann= 3 , 0 , 0
       0      .1       0   384.4    .045       0   404.4      .1       0
Bank Sta=384.4,404.4
XS Rating Curve= 0 ,0
Exp/Cntr=0.3,0.1

Type RM Length L Ch R = 1 ,54.9    ,68.4,53.1,39.7
XS GIS Cut Line= 4
     1645247.134      212978.516     1645412.815      213292.665
     1645462.518      213362.587     1645840.767      213509.168
#Sta/Elev= 30
     9.9  928.87    19.7  929.21    39.5  921.71    59.2  911.84    88.8  888.83
   128.3  849.41     148  842.59   167.7  825.24   197.3  802.89   226.9  785.94
   256.5  773.17   276.2   770.4   335.4  754.15   374.2  749.45   383.3  745.46
   393.3  744.09   403.3   746.1   412.4  750.49   431.4  753.19   628.9  758.94
   638.8  765.86   658.6   790.5   678.4  805.61   688.3  816.83     718  833.37
   727.9  841.81   797.1  882.35   816.9  897.88   826.8  904.12   846.6  913.34
#Mann= 3 , 0 , 0
       0      .1       0   383.3    .045       0   403.3     .06       0
Bank Sta=383.3,403.3
XS Rating Curve= 0 ,0
Exp/Cntr=0.3,0.1

Type RM Length L Ch R = 1 ,1.8     ,0,1.8,12.6
XS GIS Cut Line= 5
     1645240.237      212982.956     1645369.135      213349.073
     1645388.265      213355.585     1645411.973      213368.306
     1645840.767      213527.702
#Sta/Elev= 30
      10  926.47    59.7  899.37    79.6  882.67   109.5  852.86   129.4  842.26
   159.2  813.88   179.1  797.87     209  780.21   228.9  772.42   238.9  772.66
   318.5  750.88   368.2  748.31   388.1  742.56   407.3  742.67   417.3  742.53
   427.3  743.25   445.2  749.36     475  753.24   564.5  757.08     654  757.91
   673.9  759.95   683.9  765.21   693.8  779.96   703.8  798.81   713.7  808.91
   733.6  825.28   793.3  867.87   852.9  903.57   862.9  913.05   892.7  926.85
#Mann= 3 , 0 , 0
       0      .1       0   407.3    .045       0   427.3     .06       0
Bank Sta=407.3,427.3
XS Rating Curve= 0 ,0
Exp/Cntr=0.3,0.1

Chan Stop Cuts=-1
Use User Specified Reach Order=0